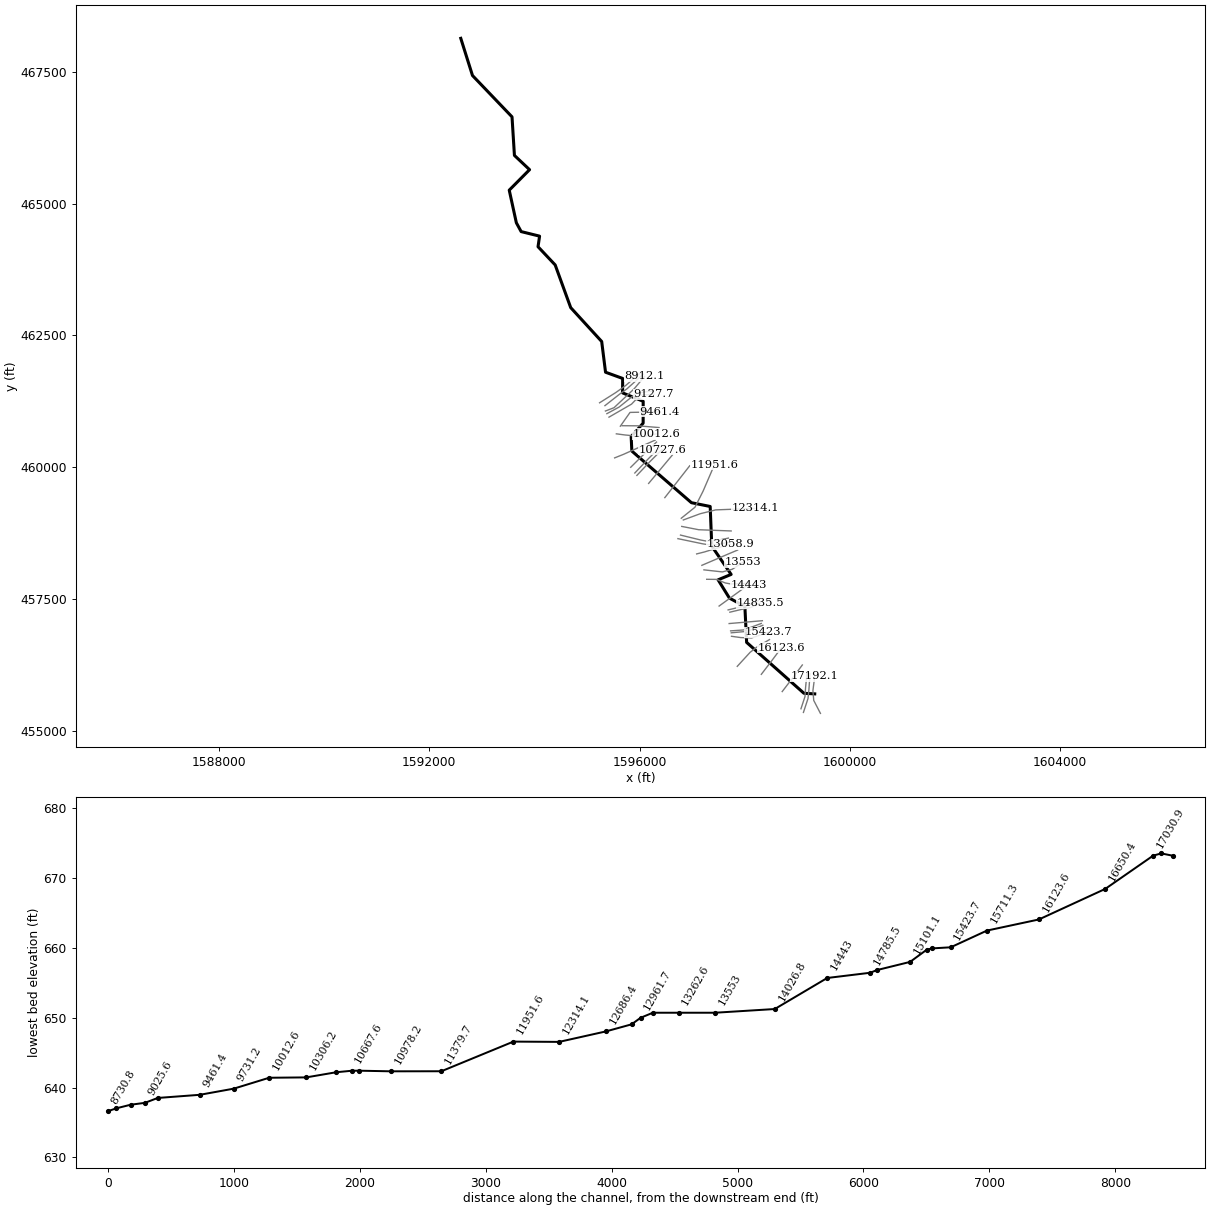
--- RaccoonCr.prj (project) ---

Proj Title=RaccoonCr
Current Plan=p01
Default Exp/Contr=0,0
English Units
Geom File=g01
Flow File=f01
Plan File=p01
BEGIN DESCRIPTION:
END DESCRIPTION:
DSS Export Rating Curves= 0
DSS Export Rating Curve Sorted= 0
DSS Export Volume Flow Curves= 0
DXF OffsetX= 0
DXF OffsetY= 0
DXF ScaleX= 0
DXF ScaleY= 0

--- RaccoonCr.p01 (plan) ---

Plan Title=Floodplain
Program Version=4.00
Geom File=g01
Flow File=f01
K Sum by GR=0
Std Step Tol=0.01
Critical Tol=0.01
Num of Std Step Trials=20
Max Error Tol=0.3
Flow Tol Ratio=0.001
Split Flow NTrial=30
Split Flow Tol=0.02
Split Flow Ratio=0.02
Log Output Level=0
Friction Slope Method=1
Unsteady Friction Slope Method=2
Unsteady Bridges Friction Slope Method=1
Global Log Level=0
CheckData=False
Run HTab=0
Run UNet=0
Run PostProcess=0
UNET Theta=0
UNET Theta Warmup=0
UNET ZTol=0
UNET ZSATol=0
UNET MxIter=0
UNET MaxInSteps=0
UNET DtIC=0
UNET DtMin=0
UNET MaxCRTS=0
UNET WFStab=0
UNET SFStab=0
UNET WFX=0
UNET SFX=0
UNET DSS MLevel=0
UNET DZMax Abort=0
UNET Convert EG Bridges=0
UNET Use Existing IB Tables=0
UNET Froude Limit=0
UNET Froude Power=0
Write IC File=0
Echo Input=False
Echo Output=False
Write Detailed=0

--- RaccoonCr.f01 (steady flow) ---

Flow Title=NFF Regression Equation
Program Version=4.10
Number of Profiles= 1
Profile Names=P100yr
River Rch & RM=RaccoonCr,Main            ,17192.1
     827
River Rch & RM=RaccoonCr,Main            ,17095.5
    1075
River Rch & RM=RaccoonCr,Main            ,15711.3
    1099
River Rch & RM=RaccoonCr,Main            ,15423.7
    1172
River Rch & RM=RaccoonCr,Main            ,13058.9
    1216
River Rch & RM=RaccoonCr,Main            ,12314.1
    1302
River Rch & RM=RaccoonCr,Main            ,11951.6
    1541
River Rch & RM=RaccoonCr,Main            ,9127.7
    1595
River Rch & RM=RaccoonCr,Main            ,5943
    1711
River Rch & RM=RaccoonCr,Main            ,5644.5
    1918
River Rch & RM=RaccoonCr,Main            ,51.6
    2040
Boundary for River Rch & Prof#=RaccoonCr,Main            , 1
Up Type= 0
Dn Type= 3
Dn Slope=0.0034
DSS Import GetInterval= 0
DSS Import GetPeak= 0
DSS Import FillOption= 0

--- RaccoonCr.g01 (geometry) ---

Geom Title=USGS 10m DEM
Program Version=4.10

River Reach=RaccoonCr       ,Main
Reach XY= 30
     1599330.925      455709.326     1599126.064      455720.611
     1598035.786      456685.021     1598002.345      457365.169
     1597708.269      457524.257     1597493.082      457870.559
     1597740.908      457972.868      1597372.74      458508.688
     1597342.514      459259.978     1596985.526      459331.809
     1595852.137      460309.969     1595839.365      460583.472
     1596067.123       460838.32     1596067.991      461252.816
      1595675.63      461412.538     1595677.713      461685.697
     1595351.861      461803.677     1595278.581      462385.715
     1594689.172      463027.642     1594393.939      463835.971
     1594067.644      464181.288     1594097.158      464381.809
     1593746.463      464468.181     1593655.318      464634.847
     1593519.901      465252.903     1593906.596      465641.047
     1593618.686       465911.41     1593572.845      466641.811
     1592820.943      467425.038     1592597.945      468129.671

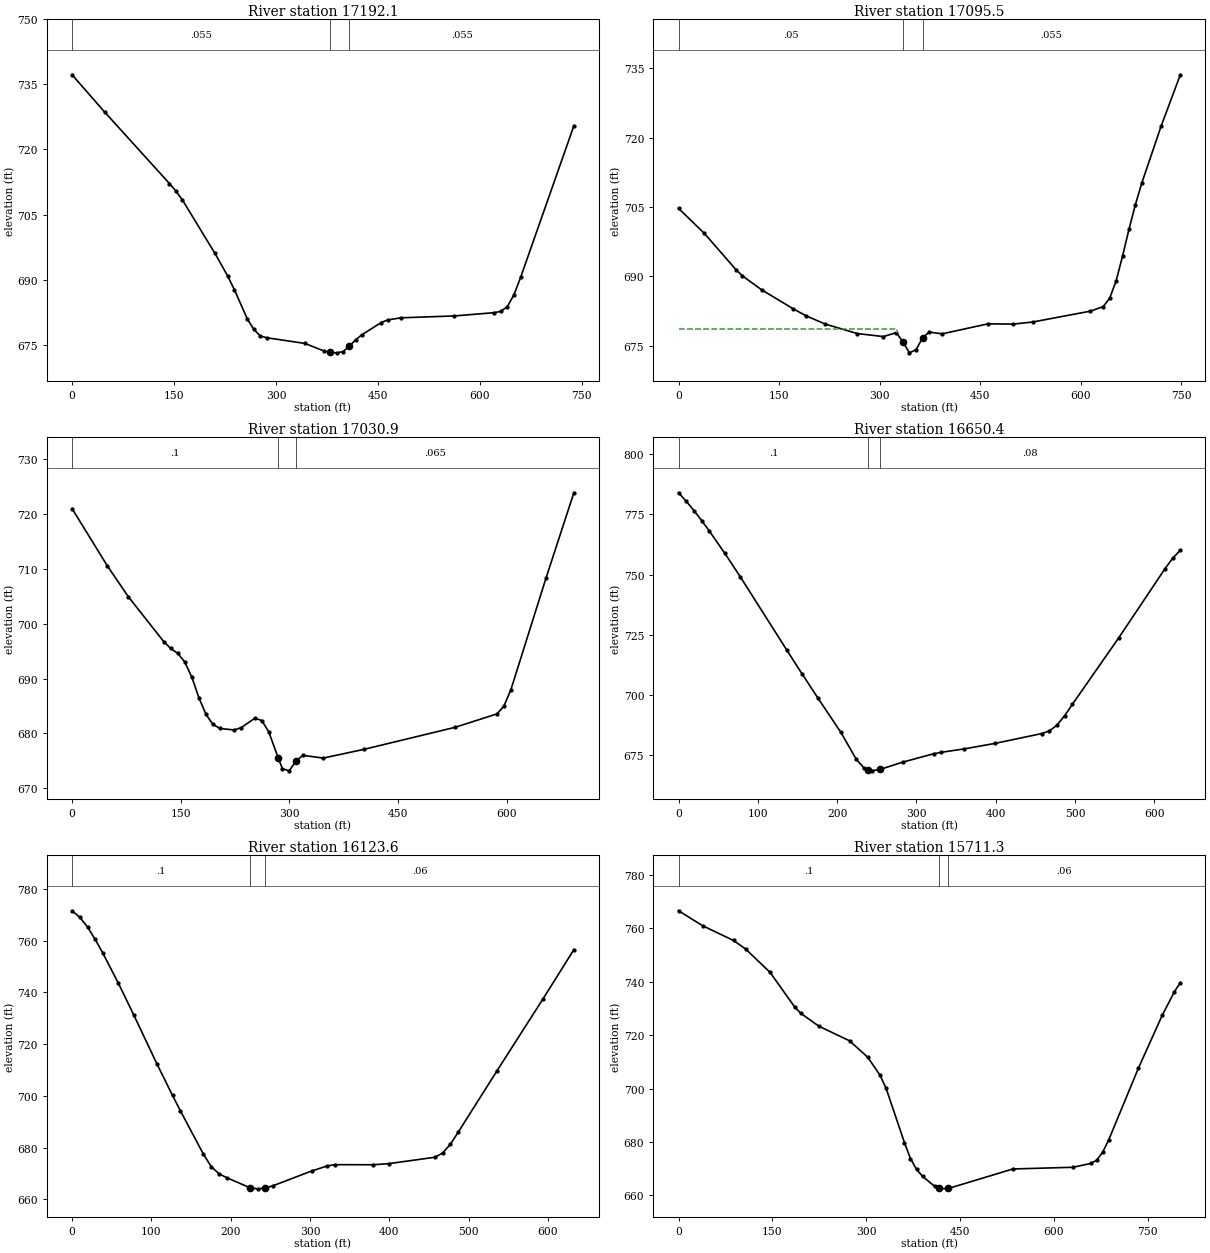
Type RM Length L Ch R = 1 ,17192.1 ,100.1,96.6,93.1
XS GIS Cut Line= 4
     1599439.736      455339.983     1599312.132       455585.86
     1599296.941      455772.492     1599331.663       456044.41
#Sta/Elev= 30
       0   737.2    47.8  728.64   143.3  712.15   152.8  710.42   162.4  708.36
   210.2  696.07   229.3  690.75   238.8  687.71   257.9  680.93   267.5  678.53
     277  677.02   286.4  676.62   342.6  675.31   370.6  673.57     380  673.25
   389.4  673.14   398.7  673.42   408.1  674.67   417.4  676.17   426.8  677.34
   454.9  680.12   464.3  680.71   483.8  681.21   562.2  681.64   620.9  682.39
   630.7  682.68   640.5   683.8   650.3  686.53   660.1  690.55   738.4  725.44
#Mann= 3 , 0 , 0
       0    .055       0     380    .045       0   408.1    .055       0
Bank Sta=380,408.1
XS Rating Curve= 0 ,0
Exp/Cntr=0.3,0.1

Type RM Length L Ch R = 1 ,17095.5 ,63.3,64.6,65.9
XS GIS Cut Line= 4
     1599116.168      455357.778     1599202.974      455619.931
     1599220.335      455784.862     1599241.168      456090.417
#Sta/Elev= 30
       0  704.73    38.1  699.38    85.7  691.47    95.2  690.14   123.8  687.13
   171.4  682.98   190.4  681.48     219   679.7   266.6  677.66   305.4  677.01
   324.9  677.86   334.7   675.8   344.4  673.49   354.2  674.18     364  676.73
   373.7  677.98   393.2   677.6   461.1  679.75   499.4  679.71   528.1  680.15
   614.3  682.51   633.4   683.5     643  685.32   652.6  689.06   662.1  694.38
   671.7  700.19   681.3  705.54   690.8  710.18   719.6  722.49   748.3  733.61
#Mann= 3 , 0 , 0
       0     .05       0   334.7    .045       0     364    .055       0
#XS Ineff= 2 , 0
          325.31  678.61
Permanent Ineff=
       F       F
Bank Sta=334.7,364
XS Rating Curve= 0 ,0
Exp/Cntr=0.3,0.1

Type RM Length L Ch R = 1 ,17030.9 ,394.4,380.5,366.6
XS GIS Cut Line= 4
     1599069.293      455427.223     1599145.682      455658.126
     1599156.099      455817.848     1599183.877      456106.042
#Sta/Elev= 30
       0  721.03    48.6   710.6    77.8  704.93   126.5  696.77   136.2   695.5
   145.9  694.61   155.6  693.03   165.4  690.25   175.1  686.52   184.8  683.49
   194.6  681.64   204.3   680.9   223.8  680.63   233.5  681.06   252.6  682.79
     262  682.34   271.5   680.3  284.62  675.54   290.3  673.57   299.7  673.17
   309.1  674.95   318.5     676   346.8   675.5   403.3   677.1   528.7  681.11
   586.6  683.56   596.3     685   605.9  687.99   654.2  708.29   692.8  723.92
#Mann= 3 , 0 , 0
       0      .1       0  284.62    .045       0   309.1    .065       0
Bank Sta=284.62,309.1
XS Rating Curve= 0 ,0
Exp/Cntr=0.3,0.1

Type RM Length L Ch R = 1 ,16650.4 ,526.6,526.8,526.3
XS GIS Cut Line= 3
     1598712.581       455753.25     1598914.779      456015.765
     1599095.335      456257.084
#Sta/Elev= 30
       0     784     9.8  780.44    19.5  776.59    29.2  772.45      39  768.04
    58.5  758.76      78  749.02   136.4  718.66   155.9  708.67   175.4  698.84
   204.7  684.42   224.2  673.17   233.9  669.59   239.1  668.96   243.6  668.41
   254.1  668.99   282.6  672.02   321.6  675.49   331.4  676.11   360.5  677.55
   399.4  679.83   457.8  683.89   467.5  684.97   477.2  687.38   486.9  691.32
   496.6  696.02     555  723.64   613.3  752.36     623  756.69   632.8  760.16
#Mann= 3 , 0 , 0
       0      .1       0   239.1    .045       0   254.1     .08       0
Bank Sta=239.1,254.1
XS Rating Curve= 0 ,0
Exp/Cntr=0.3,0.1

Type RM Length L Ch R = 1 ,16123.6 ,417.6,412.3,406.2
XS GIS Cut Line= 3
     1598315.011      456079.639      1598517.21      456342.153
     1598697.765      456583.473
#Sta/Elev= 30
       0  771.53     9.8  769.01    19.5  765.25    29.2  760.43      39  755.05
    58.5  743.46      78  731.13   107.2  712.22   126.7  700.14   136.4  694.32
   165.7  677.41   175.4  672.67   185.2  669.88   194.9  668.36   224.2  664.49
   233.9  664.04   243.5  664.33   253.4  665.24   302.1  670.93   321.6  672.87
   331.4  673.38     380  673.36   399.4  673.78   457.8  676.26   467.5  677.94
   477.2  681.33   486.9  685.91   535.5  709.49   593.9  737.48   632.8   756.5
#Mann= 3 , 0 , 0
       0      .1       0   224.2    .045       0   243.5     .06       0
Bank Sta=224.2,243.5
XS Rating Curve= 0 ,0
Exp/Cntr=0.3,0.1

Type RM Length L Ch R = 1 ,15711.3 ,300.9,287.7,272.8
XS GIS Cut Line= 4
     1597857.488      456231.042     1598102.279      456496.667
     1598239.432       456602.57     1598470.335      456737.987
#Sta/Elev= 30
       0  766.58      39  760.92    87.9  755.46   107.4  752.23   146.4   743.5
   185.5  730.61   195.2  728.22   224.5  723.34   273.4  717.89   302.6   711.7
   322.2  704.97   331.9  700.04   361.2  679.74   370.8  673.79   380.5  669.72
   390.1  667.13   409.4   663.4   416.4  662.73   428.6  662.45   431.4  662.59
   534.5  669.89   630.1  670.52   658.8  671.94   668.3  673.11   677.9  676.12
   687.5  680.67   735.3   707.7   773.5  727.56   792.6  736.18   802.2  739.72
#Mann= 3 , 0 , 0
       0      .1       0   416.4    .045       0   431.4     .06       0
Bank Sta=416.4,431.4
XS Rating Curve= 0 ,0
Exp/Cntr=0.3,0.1

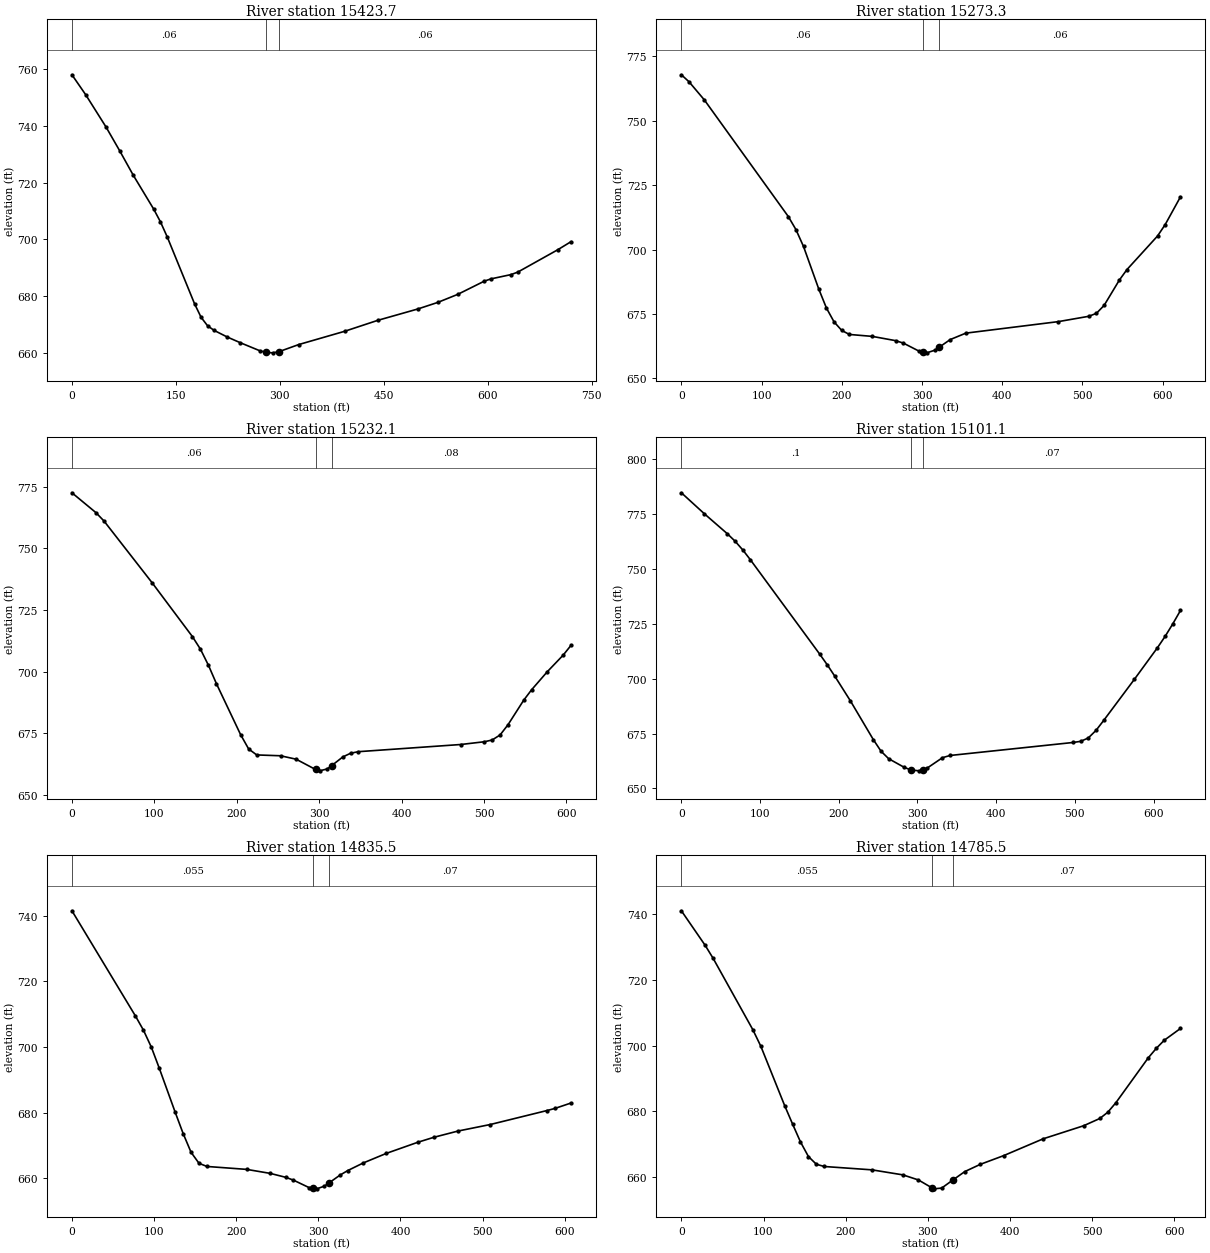
Type RM Length L Ch R = 1 ,15423.7 ,145.2,150.3,155.1
XS GIS Cut Line= 4
     1597748.113      456800.487      1597923.46      456776.181
     1598130.057      456769.237     1598449.502       456875.14
#Sta/Elev= 30
       0  757.93    19.7  750.97    49.2  739.55    68.8  731.23    88.5  722.58
     118  710.65   127.8  706.14   137.7  700.77     177  677.31   186.4  672.57
   195.8  669.57   205.2  667.96     224  665.65   242.8  663.64     271  660.81
   280.4  660.19   289.8  660.06   299.2  660.51   327.4  662.98   393.4  667.63
   441.4   671.5   499.1  675.49     528  677.81   556.8  680.64   595.3  685.31
   604.9   686.1   633.7   687.6   643.4  688.47     701  696.32   720.3  699.19
#Mann= 3 , 0 , 0
       0     .06       0   280.4    .045       0   299.2     .06       0
Bank Sta=280.4,299.2
XS Rating Curve= 0 ,0
Exp/Cntr=0.3,0.1

Type RM Length L Ch R = 1 ,15273.3 ,39.1,41.2,43.4
XS GIS Cut Line= 4
     1597742.904      456866.459     1597989.432      456889.028
     1598140.474      456927.223     1598343.599       457008.82
#Sta/Elev= 30
       0  767.87     9.5  765.17    28.6  758.13   133.3  712.84   142.8  707.79
   152.3   701.2   171.4  684.61   180.9  677.28   190.4  671.91     200  668.59
   209.5  667.04     238  666.29     267  664.64   276.8  663.68   296.2  660.58
  301.77  660.23     306   659.9   315.7  660.89   321.1     662   335.2  665.05
   354.7  667.55     470  672.02     508  674.09   517.6  675.26   527.1  678.32
   546.1  688.15   555.6  692.24   593.7  705.26   603.2  709.67   622.3  720.47
#Mann= 3 , 0 , 0
       0     .06       0  301.77    .045       0   321.1     .06       0
Bank Sta=301.77,321.1
XS Rating Curve= 0 ,0
Exp/Cntr=0.3,0.1

Type RM Length L Ch R = 1 ,15232.1 ,136.5,131,125.2
XS GIS Cut Line= 4
     1597730.752      456902.917     1597973.807      456920.278
     1598098.807      456963.681     1598314.085      457043.542
#Sta/Elev= 30
       0   772.6    29.2  764.52      39   761.1    97.5  735.98   146.2   714.2
     156  709.06   165.7  702.52   175.4  695.04   204.7  674.38   214.4  668.59
   224.2  666.16   253.1  665.82     272  664.43  295.55  660.26   300.4   659.7
   309.8  660.47   315.1   661.8   328.7  665.35   338.2  666.85   347.6  667.48
   471.7  670.39   500.4  671.51   509.9  672.22   519.5  674.26   529.1   678.4
   548.2  688.39   557.8  692.63   576.9  699.98     596  706.65   605.6  710.66
#Mann= 3 , 0 , 0
       0     .06       0  295.55    .045       0   315.1     .08       0
Bank Sta=295.55,315.1
XS Rating Curve= 0 ,0
Exp/Cntr=0.3,0.1

Type RM Length L Ch R = 1 ,15101.1 ,262.8,265.7,268.2
XS GIS Cut Line= 2
     1597702.974      457041.806     1598334.918      457095.626
#Sta/Elev= 30
       0   784.8    29.3   775.2    58.5  766.09    68.3   762.7    78.1   758.7
    87.8   754.2   175.6   711.3   185.4  706.32   195.2  701.01   214.7  689.94
   243.9  672.23   253.7  666.93   263.4  663.51     283   659.6   291.7  658.35
   302.5  657.97   306.7   658.5   312.2  659.19   331.8  663.97   341.5  664.98
   497.6   670.9   507.4  671.42   517.1  672.97   526.9  676.42   536.7  680.98
   575.7  699.74     605  714.15   614.7   719.3   624.5  725.03   634.2  731.11
#Mann= 3 , 0 , 0
       0      .1       0   291.7    .045       0   306.7     .07       0
Bank Sta=291.7,306.7
XS Rating Curve= 0 ,0
Exp/Cntr=0.3,0.1

Type RM Length L Ch R = 1 ,14835.5 ,50.1,49.9,49.9
XS GIS Cut Line= 4
     1597716.863      457257.084     1597942.557      457310.903
     1598117.904      457347.362     1598294.988      457432.431
#Sta/Elev= 30
       0  741.54    77.3  709.48      87  705.18    96.7  699.96   106.3  693.58
   125.7  680.14   135.4  673.64     145  667.94   154.7  664.57   164.4  663.61
   212.7  662.72   241.4   661.5   260.3   660.3   269.7  659.44   288.6  657.18
  293.76  656.96     298  656.79   307.4  657.62   312.6  658.53   326.3  660.96
   335.7  662.35   354.6  664.67   382.8   667.6   420.9  670.97   440.6   672.5
   470.1  674.41   509.4   676.4   578.1  680.64   587.9  681.29   607.6  682.95
#Mann= 3 , 0 , 0
       0    .055       0  293.76    .045       0   312.6     .07       0
Bank Sta=293.76,312.6
XS Rating Curve= 0 ,0
Exp/Cntr=0.3,0.1

Type RM Length L Ch R = 1 ,14785.5 ,332.6,342.5,351.7
XS GIS Cut Line= 4
     1597683.877      457300.487     1597909.571      457354.306
     1598084.918      457390.765     1598262.002      457475.834
#Sta/Elev= 30
       0  741.05      29  730.52    38.7  726.56      87  704.86    96.7  699.84
   125.7  681.78   135.4  676.13     145   670.7   154.7  666.24   164.4  663.89
     174  663.22     232   662.2   269.7  660.67   288.6  659.12  305.72  656.63
   307.4  656.42   316.9  656.65   330.2  659.05   345.1  661.68     364  663.88
   392.3  666.52   440.6  671.66   489.7  675.62   509.4  677.83   519.2  679.75
     529  682.64   568.3  696.26   578.1  699.16   587.9  701.65   607.6  705.23
#Mann= 3 , 0 , 0
       0    .055       0  305.72    .045       0   330.2     .07       0
Bank Sta=305.72,330.2
XS Rating Curve= 0 ,0
Exp/Cntr=0.3,0.1

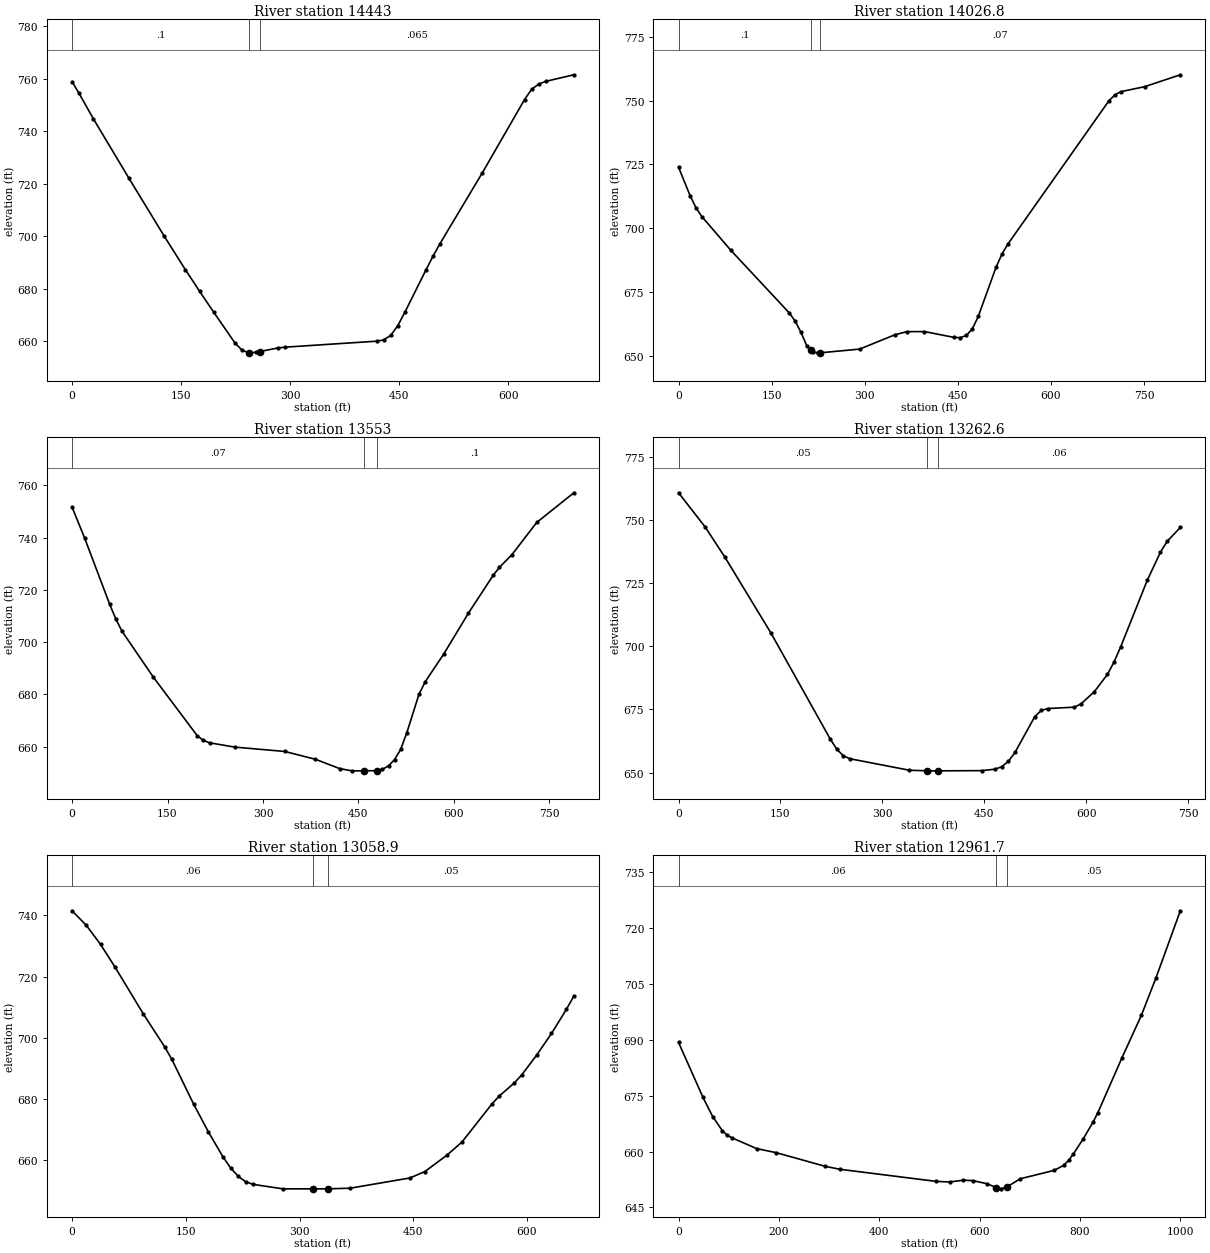
Type RM Length L Ch R = 1 ,14443   ,439.9,416.3,389.7
XS GIS Cut Line= 3
     1597512.002      457373.403     1597843.599      457612.987
     1598071.029      457777.917
#Sta/Elev= 30
       0   758.8     9.7  754.32    29.2  744.72    77.9   722.2   126.6   700.1
   155.8  687.31   175.3   679.1   194.8   671.1     224  659.43   233.8  656.65
   242.9  655.73   243.5  655.67   253.2  655.89   257.9  656.16   282.5  657.49
   292.2  657.82   418.8   660.1   428.5  660.58   438.2  662.33   447.8  665.96
   457.5  671.04   486.6  687.19   496.3   692.4     506  697.24   564.1  724.11
   622.2  752.01   631.9  755.89   641.6  757.87   651.3  758.91     690  761.42
#Mann= 3 , 0 , 0
       0      .1       0   242.9    .045       0   257.9    .065       0
Bank Sta=242.9,257.9
XS Rating Curve= 0 ,0
Exp/Cntr=0.3,0.1

Type RM Length L Ch R = 1 ,14026.8 ,454.7,473.7,492
XS GIS Cut Line= 5
      1597275.89      457880.348      1597463.39      457878.612
     1597630.057      457810.903     1597734.224      457791.806
     1598069.293      457802.223
#Sta/Elev= 30
       0  723.92    18.8  712.66    28.1  708.04    37.5   704.6    84.4  691.34
   178.1  666.94   187.5  663.81     197  659.41   206.4   654.1   213.4  652.32
   215.9  651.68   225.4  651.23   228.4  651.25   291.7  652.69   348.5  658.29
   367.4  659.51   396.3  659.56   444.4  657.24     454  657.18   463.7  658.02
   473.3  660.57   482.9  665.46   511.6  684.76   521.2  689.93   530.8  693.87
   693.6  749.97   703.2  752.25   712.8  753.49   751.1  755.45   808.5   760.1
#Mann= 3 , 0 , 0
       0      .1       0   213.4    .045       0   228.4     .07       0
Bank Sta=213.4,228.4
XS Rating Curve= 0 ,0
Exp/Cntr=0.3,0.1

Type RM Length L Ch R = 1 ,13553   ,286.6,290.5,293.5
XS GIS Cut Line= 4
     1597223.286      458059.167     1597574.849      458020.105
     1597759.745      458069.584     1597965.474      458199.792
#Sta/Elev= 30
       0  751.63    19.6  739.89      59  714.51    68.8  708.79    78.6  704.09
   127.7  686.57   196.5  664.22   206.3  662.36   216.2  661.43   255.5  659.79
   334.1  658.12   382.4  655.13   420.7  651.55   439.9   650.7     459   650.7
   478.6  650.78   487.7  651.25   497.3  652.64   506.8  654.98   516.4   658.9
     526  665.22   545.1  679.92   554.9  684.78   584.1  695.41     623  711.08
     662  725.61   671.7  728.61   691.2  733.41   730.2  745.77   788.6  757.13
#Mann= 3 , 0 , 0
       0     .07       0     459    .045       0   478.6      .1       0
Bank Sta=459,478.6
XS Rating Curve= 0 ,0
Exp/Cntr=0.3,0.1

Type RM Length L Ch R = 1 ,13262.6 ,206.6,203.6,201.3
XS GIS Cut Line= 3
     1597184.224      458145.105     1597684.224      458358.647
     1597863.911      458434.167
#Sta/Elev= 30
       0   760.7    38.8  747.32      68  735.34   135.9  705.28   223.3  663.28
     233  659.23   242.7  656.62   252.4  655.48   339.8  650.94   366.4  650.71
   368.9   650.7   381.4   650.7   446.6  650.78     466  651.36   475.7  652.34
   485.4  654.44   495.2  657.96   524.3  672.12     534   674.6   543.7  675.35
   582.7  675.89   592.4   677.2   611.9  681.96   631.4  688.88   641.2  693.86
   650.9   699.8   689.9  726.06   709.4  737.25   719.1  741.45   738.6  747.01
#Mann= 3 , 0 , 0
       0     .05       0   366.4    .045       0   381.4     .06       0
Bank Sta=366.4,381.4
XS Rating Curve= 0 ,0
Exp/Cntr=0.3,0.1

Type RM Length L Ch R = 1 ,13058.9 ,103.7,97.2,90.6
XS GIS Cut Line= 3
     1597085.265      458361.251     1597231.099      458397.709
     1597720.682      458546.147
#Sta/Elev= 30
       0  741.45    18.8  736.69    37.6  730.46    56.4  723.18      94  707.79
   122.1  697.06   131.5     693   160.2  678.43   179.8  669.29   199.5  660.95
   209.4  657.44   219.2  654.77     229  653.02   238.9  652.15   278.2   650.7
   317.6   650.7   337.2   650.7   366.8  650.91   445.5  654.24   465.2  656.31
   494.7  661.74   514.3  665.97   553.7  678.36   563.5     681   583.2  685.22
     593  687.84   612.7   694.3   632.4   701.4   652.1   709.3   661.9  713.61
#Mann= 3 , 0 , 0
       0     .06       0   317.6    .045       0   337.2     .05       0
Bank Sta=317.6,337.2
XS Rating Curve= 0 ,0
Exp/Cntr=0.3,0.1

Type RM Length L Ch R = 1 ,12961.7 ,71.1,72,73
XS GIS Cut Line= 5
     1596728.495      458650.313     1597205.057      458551.355
     1597293.599      458538.334     1597465.474      458538.334
      1597712.87      458585.209
#Sta/Elev= 30
       0  689.33    48.7  674.56    68.1  669.38    87.6  665.55    97.4  664.36
   107.1  663.65   155.8  660.79   194.7   659.7     292  656.04   321.2  655.24
   513.6  651.98   540.4  651.83   567.3   652.3   585.8   652.2   614.4  651.37
   633.5  650.31   643.1  649.98   654.8  650.54   681.3   652.7   748.1  654.93
   767.5  656.28   777.2  657.62   786.8  659.36   806.2  663.37   825.6  667.81
   835.3  670.37   883.7  685.23   922.4  696.65   951.5  706.72   999.9  724.71
#Mann= 3 , 0 , 0
       0     .06       0   633.5    .045       0   654.8     .05       0
Bank Sta=633.5,654.8
XS Rating Curve= 0 ,0
Exp/Cntr=0.3,0.1

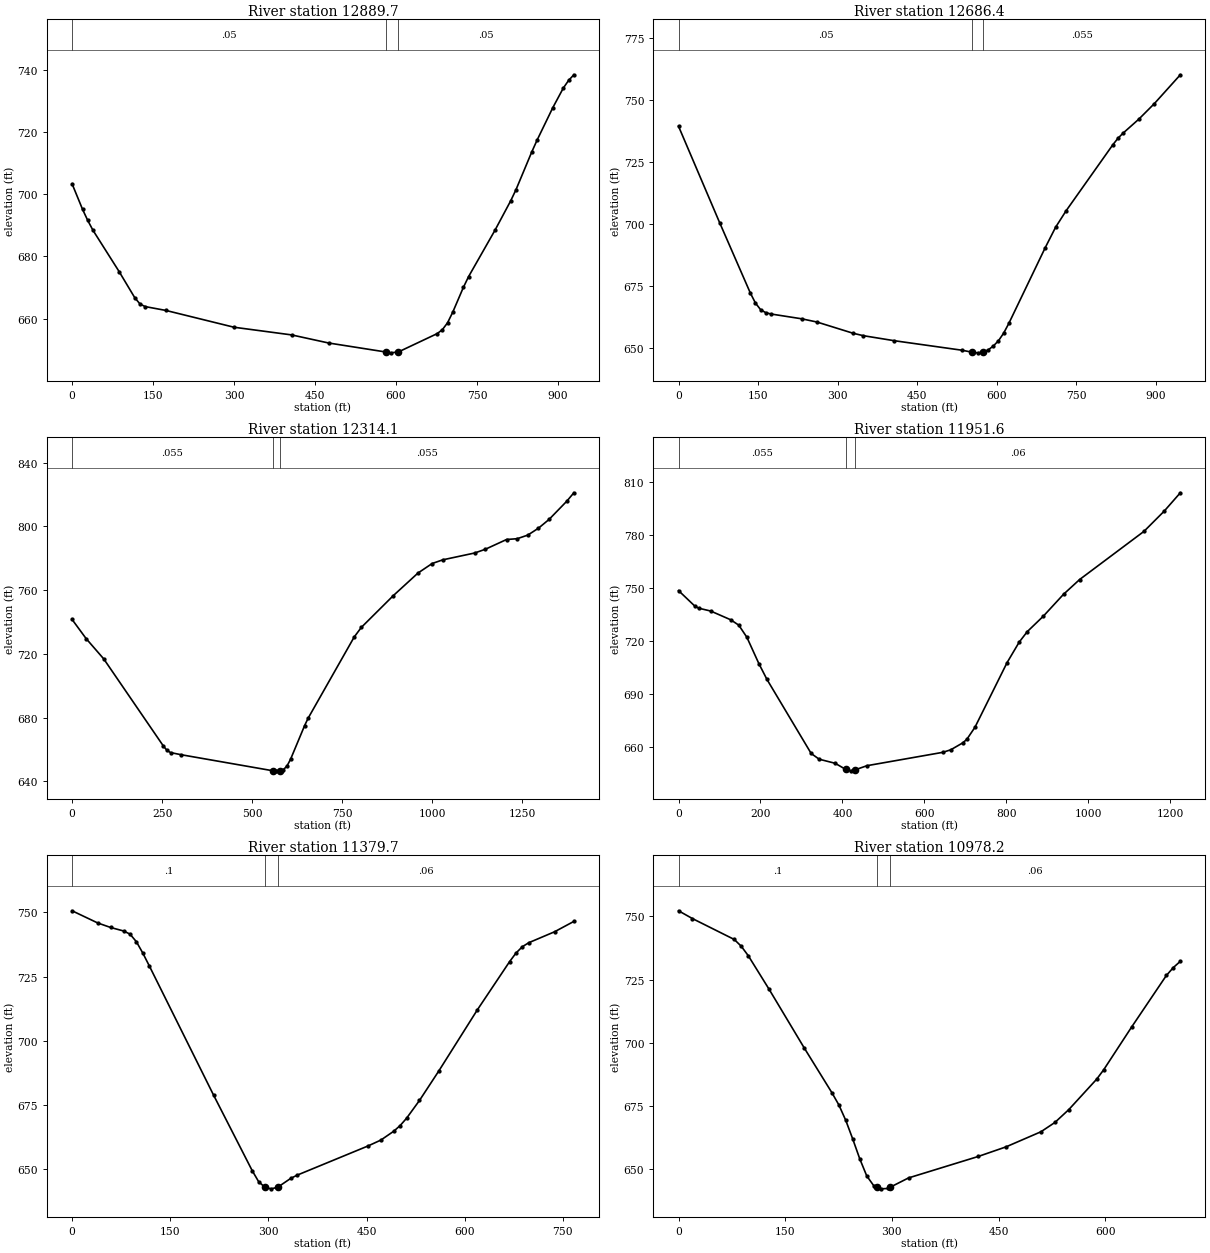
Type RM Length L Ch R = 1 ,12889.7 ,204.7,203.2,201.2
XS GIS Cut Line= 5
     1596777.974      458718.022      1597163.39      458624.272
     1597259.745      458606.042     1597460.265      458613.855
     1597689.432       458660.73
#Sta/Elev= 30
       0  703.31    19.4  695.11      29  691.55    38.7  688.39    87.1  675.14
   116.1  666.74   125.8  664.72   135.4  663.89   174.1  662.64   299.9  657.26
   406.5   654.8   475.1   652.2   580.7  649.32   590.3  649.04  604.34  649.33
   676.3  655.22   685.8  656.48   695.4  658.69   705.1  662.13   724.6  670.02
   734.4  673.54   783.1  688.36   812.4  697.87   822.1  701.41   851.3  713.52
   861.1   717.3   890.3  727.75   909.8  734.06   919.6  736.51   929.3  738.31
#Mann= 3 , 0 , 0
       0     .05       0   580.7    .045       0  604.34     .05       0
Bank Sta=580.7,604.34
XS Rating Curve= 0 ,0
Exp/Cntr=0.3,0.1

Type RM Length L Ch R = 1 ,12686.4 ,365.7,372.3,378.6
XS GIS Cut Line= 3
     1596801.411      458882.084     1597124.328      458819.584
     1597741.515      458796.147
#Sta/Elev= 30
       0  739.39    77.4  700.59   135.4  672.17   145.1   668.1   154.8  665.44
   164.4  664.24   174.1   663.7   232.2  661.76   261.2  660.45   328.9  655.95
   348.5  654.95   407.3  652.91   534.8  649.08   554.4  648.26   564.2  648.03
   574.2  648.27   583.8  649.18   593.6  650.75   603.4  652.88   613.2  655.95
     623  659.89   691.6  690.41   711.2  698.66   730.9  705.27   819.1  731.91
   828.9  734.56   838.7  736.66   868.1  742.24   897.5  748.53   946.5  760.16
#Mann= 3 , 0 , 0
       0     .05       0   554.4    .045       0   574.2    .055       0
Bank Sta=554.4,574.2
XS Rating Curve= 0 ,0
Exp/Cntr=0.3,0.1

Type RM Length L Ch R = 1 ,12314.1 ,342.9,362.5,380.5
XS GIS Cut Line= 4
     1596831.359       459004.48     1597152.083      459122.446
      1597447.45      459195.521      1598194.64       459223.23
#Sta/Elev= 30
       0   741.6      39  729.58    87.9  716.84   253.9  662.02   263.6  659.38
   273.4  658.01   302.7  656.66   557.7  646.58   567.5  646.53   577.3  646.62
   587.1  647.29   596.9  649.57   606.7  653.71     646     675   655.8  679.65
   783.7  730.61   803.4   736.6     892  756.51   960.8  770.75  1000.2  776.73
  1029.7  779.04  1118.2  783.32  1147.8  785.67  1206.8   791.8  1236.3   792.3
  1265.8  794.57  1295.3  798.89  1324.8   804.4    1374  815.84  1393.7  821.14
#Mann= 3 , 0 , 0
       0    .055       0   557.7    .045       0   577.3    .055       0
Bank Sta=557.7,577.3
XS Rating Curve= 0 ,0
Exp/Cntr=0.3,0.1

Type RM Length L Ch R = 1 ,11951.6 ,575.8,571.9,568.3
XS GIS Cut Line= 4
     1596792.297      459037.032     1597052.713      459245.365
     1597206.793      459549.185      1597425.31      460054.388
#Sta/Elev= 30
       0  748.69    39.2  740.04      49  738.74    78.5  737.11   127.5  732.14
   147.1  729.09   166.8  722.24   196.2  707.25   215.8  698.36   323.7  656.41
   343.2  653.16   382.2  650.85  408.31  647.34   421.1  646.57   430.8  647.13
     460  649.49     645  657.06   664.4   658.5   693.8  662.44   703.6  664.44
   723.3  671.21   801.9  707.94   831.4  719.51   851.1  725.45   890.4  734.23
   939.5  746.59   978.9  754.98  1136.1   782.3  1185.3  793.73  1224.6  804.12
#Mann= 3 , 0 , 0
       0    .055       0  408.31    .045       0   430.8     .06       0
Bank Sta=408.31,430.8
XS Rating Curve= 0 ,0
Exp/Cntr=0.3,0.1

Type RM Length L Ch R = 1 ,11379.7 ,402.1,401.6,400.6
XS GIS Cut Line= 2
     1596479.797      459427.657     1596952.887      460030.956
#Sta/Elev= 30
       0  750.63    39.3  745.87      59  744.12    78.6  742.77    88.5  741.55
    98.3  738.57   108.1  734.15     118  729.17   216.2  678.84   275.2  649.43
     285  645.15   294.9  642.86   304.7  642.33   314.5  643.01   334.2  646.42
     344  647.67   452.1  659.02   471.8  661.32   491.5  664.77   501.3  666.98
   511.1  669.83   530.8  676.75   560.3  688.22   619.2  712.03   668.4  730.78
   678.2  734.14     688  736.64   697.9   738.2   737.2  742.45   766.7  746.49
#Mann= 3 , 0 , 0
       0      .1       0   294.9    .045       0   314.5     .06       0
Bank Sta=294.9,314.5
XS Rating Curve= 0 ,0
Exp/Cntr=0.3,0.1

Type RM Length L Ch R = 1 ,10978.2 ,251.5,250.6,248.4
XS GIS Cut Line= 2
     1596171.637      459696.754     1596625.196      460237.119
#Sta/Elev= 30
       0  752.25    19.6  749.16    78.4   740.9    88.2  738.22      98  734.51
   127.4  721.18   176.4  698.17   215.6  680.34   225.4   675.5   235.2  669.34
     245  661.96   254.8  654.18   264.6  647.44   274.4  643.58  278.65  642.99
   284.2  642.32     294  642.46   296.8  642.85   323.4  646.64   421.3  655.11
   460.5  658.92   509.5  664.88   529.1  668.55   548.7  673.65   587.9  685.68
   597.7  689.37   636.9  706.24   685.9  726.68   695.7  729.81   705.5  732.27
#Mann= 3 , 0 , 0
       0      .1       0  278.65    .045       0   296.8     .06       0
Bank Sta=278.65,296.8
XS Rating Curve= 0 ,0
Exp/Cntr=0.3,0.1

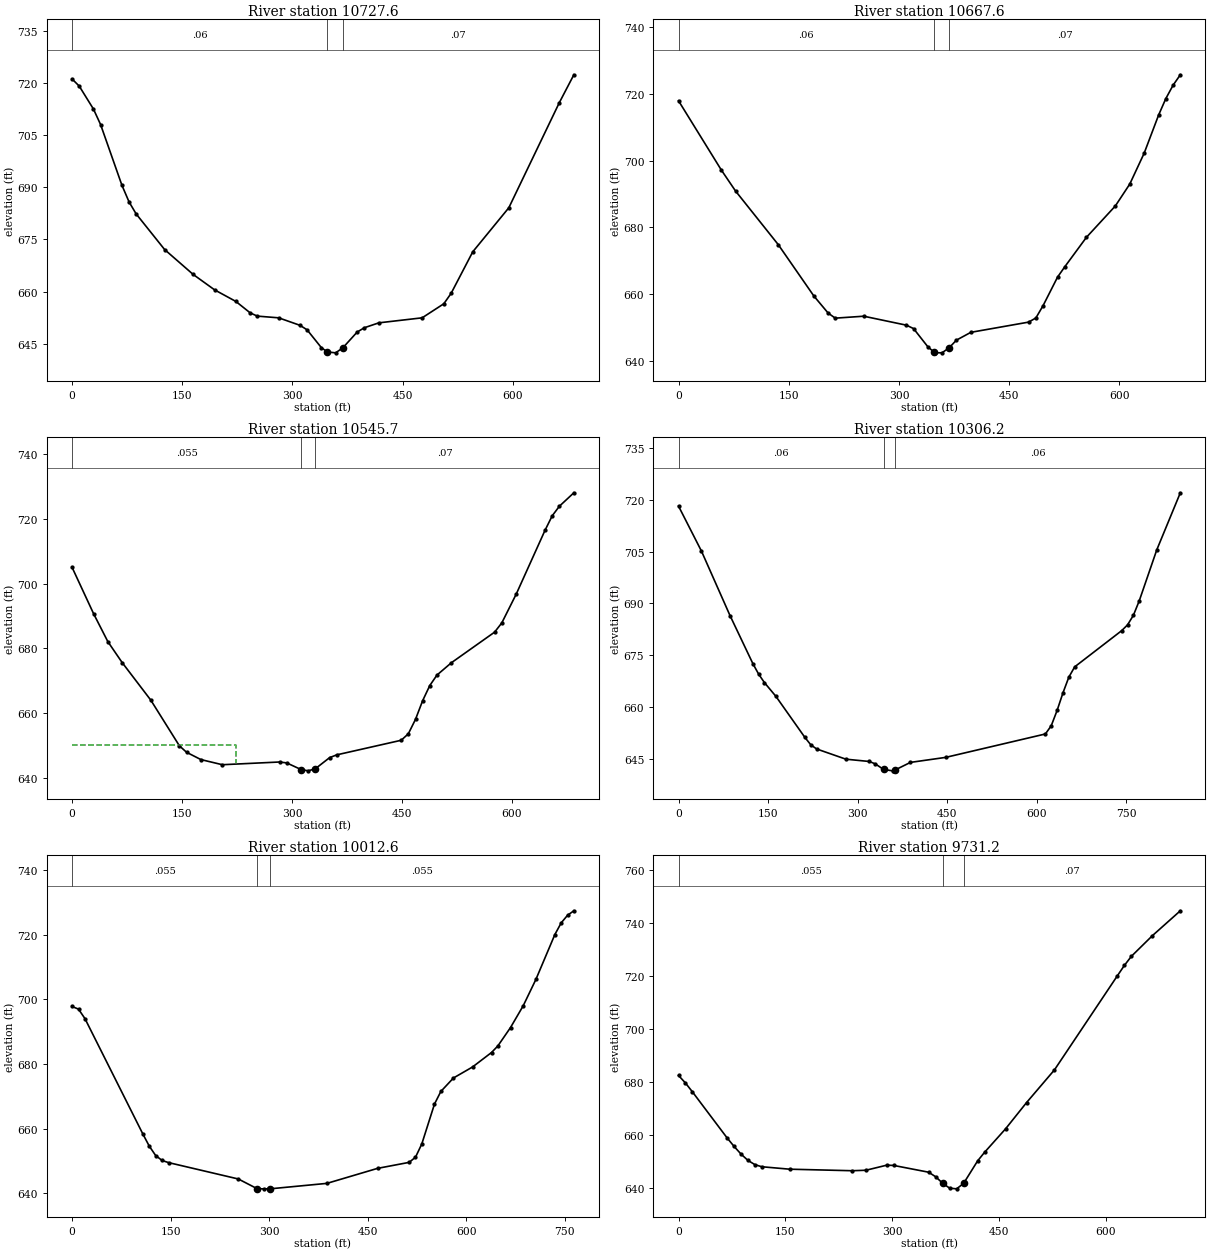
Type RM Length L Ch R = 1 ,10727.6 ,60,60,60.1
XS GIS Cut Line= 3
     1595948.113      459848.664     1596202.019      460115.591
     1596425.543      460336.945
#Sta/Elev= 30
       0  721.09     9.7  719.06    29.1  712.45    38.8  708.01    67.9  690.53
    77.6  685.76    87.2  682.33     126  672.08   164.8  664.94   193.9  660.52
     223  657.17   242.4   653.9   252.1  652.96   281.2  652.47   310.2  650.32
   319.9  649.02   339.3  643.91   347.5  642.67   358.7  642.41   368.4  643.82
   388.1  648.39   397.9  649.63   417.6  651.03   476.5  652.47     506  656.51
   515.9  659.49   545.4  671.44   594.5   684.1   663.3  714.33     683   722.3
#Mann= 3 , 0 , 0
       0     .06       0   347.5    .045       0   368.4     .07       0
Bank Sta=347.5,368.4
XS Rating Curve= 0 ,0
Exp/Cntr=0.3,0.1

Type RM Length L Ch R = 1 ,10667.6 ,122.6,121.9,121.4
XS GIS Cut Line= 3
      1595909.05      459894.237     1596162.956      460161.164
     1596386.481      460382.518
#Sta/Elev= 30
       0  717.96    58.2  697.22    77.6  690.91   135.7  674.85   184.2  659.44
   203.6  654.33   213.3   652.8   252.1  653.38   310.2  650.69   319.9  649.67
   339.3  644.23  347.28  642.69     349   642.4   358.7  642.42   368.4  643.93
   378.2   646.2   397.9  648.55   476.5  651.61   486.4  652.86   496.2  656.55
   515.9  665.11   525.7  668.19   555.2  677.03   594.5  686.42   614.2     693
   633.8  702.26   653.5  713.72   663.3  718.64   673.2  722.65     683  725.76
#Mann= 3 , 0 , 0
       0     .06       0  347.28    .045       0   368.4     .07       0
Bank Sta=347.28,368.4
XS Rating Curve= 0 ,0
Exp/Cntr=0.3,0.1

Type RM Length L Ch R = 1 ,10545.7 ,247.5,239.4,231.1
XS GIS Cut Line= 3
     1595830.925      460002.744     1596178.147      460345.626
     1596321.377      460480.174
#Sta/Elev= 30
       0  705.03    29.3  690.74    48.8  682.09    68.3  675.63   107.4  664.02
   146.4  649.92   156.2  647.92   175.7  645.67     205  644.08     283  644.92
   292.8  644.64   312.3   642.6   322.1  642.19   331.8  642.83   351.4  646.28
   361.1  647.13     449  651.63   458.7  653.63   468.5   658.1   478.2  663.84
     488  668.54   497.8  671.77   517.5  675.58   576.4  685.02   586.2  687.87
   605.9  696.77   645.2  716.48     655  720.95   664.8  723.91   684.5  728.05
#Mann= 3 , 0 , 0
       0    .055       0   312.3    .045       0   331.8     .07       0
#XS Ineff= 2 , 0
          223.56  650.11
Permanent Ineff=
       F       F
Bank Sta=312.3,331.8
XS Rating Curve= 0 ,0
Exp/Cntr=0.3,0.1

Type RM Length L Ch R = 1 ,10306.2 ,304.8,293.6,281.7
XS GIS Cut Line= 3
     1595524.936      460180.695     1595694.206      460247.969
     1596295.335      460517.067
#Sta/Elev= 30
       0   718.2    38.4  705.16    86.3  686.45   124.6  672.52   134.2   669.5
   143.8  667.06     163  663.08   211.6  651.17   221.5  649.02   231.3   647.8
   280.4  644.83   319.8  644.16   329.6  643.47   343.8  641.84   358.8  641.45
  362.22  641.65   388.6   643.9   447.6  645.35   614.7  652.14   624.5  654.52
   634.3  658.95   644.2  664.08     654  668.62   663.8   671.6   742.5  682.09
   752.3  683.76   762.1  686.52     772  690.76   801.4  705.55   840.8  722.07
#Mann= 3 , 0 , 0
       0     .06       0   343.8    .045       0  362.22     .06       0
Bank Sta=343.8,362.22
XS Rating Curve= 0 ,0
Exp/Cntr=0.3,0.1

Type RM Length L Ch R = 1 ,10012.6 ,280.9,281.5,280.6
XS GIS Cut Line= 4
     1595557.488      460636.424     1595722.418      460614.723
      1596067.47      460582.171     1596312.696      460634.254
#Sta/Elev= 30
       0  697.82     9.8     697    19.6  694.07   107.6  658.42   117.4  654.64
   127.2  651.71     137  650.17   146.8  649.52     253  644.45   281.9  641.42
   291.5   641.4   301.1   641.4   387.8  643.09   464.8  647.73   512.9  649.59
   522.6  651.18   532.2  655.28   551.5  667.63   561.2  671.53   580.4   675.7
   609.4   679.1   638.3  683.58   647.9   685.6   667.2   691.3   686.5  698.03
   705.8  706.18   734.7  720.08   744.4  723.71     754  726.04   763.6  727.43
#Mann= 3 , 0 , 0
       0    .055       0   281.9    .045       0   301.1    .055       0
Bank Sta=281.9,301.1
XS Rating Curve= 0 ,0
Exp/Cntr=0.3,0.1

Type RM Length L Ch R = 1 ,9731.2  ,267.7,269.7,272.1
XS GIS Cut Line= 3
     1595666.429       460790.07     1595968.512      460788.334
     1596369.554      460755.348
#Sta/Elev= 30
       0  682.52     9.7   679.7    19.5  676.36    68.2  659.01      78  655.81
    87.7  652.94    97.4  650.56   107.2  648.95   116.9  648.16   155.9  647.24
   243.6  646.66   263.1  646.84   292.3  648.75   302.1  648.65   351.2   646.1
     361  644.38   370.8  641.96   380.6  640.09   390.4  639.84   400.2  641.88
   419.9  650.36   429.7  653.61   459.1  662.42   488.6  672.32   527.8  684.64
   616.2   720.1     626  723.98   635.8   727.4   665.2  735.15   704.5  744.54
#Mann= 3 , 0 , 0
       0    .055       0   370.8    .045       0   400.2     .07       0
Bank Sta=370.8,400.2
XS Rating Curve= 0 ,0
Exp/Cntr=0.3,0.1

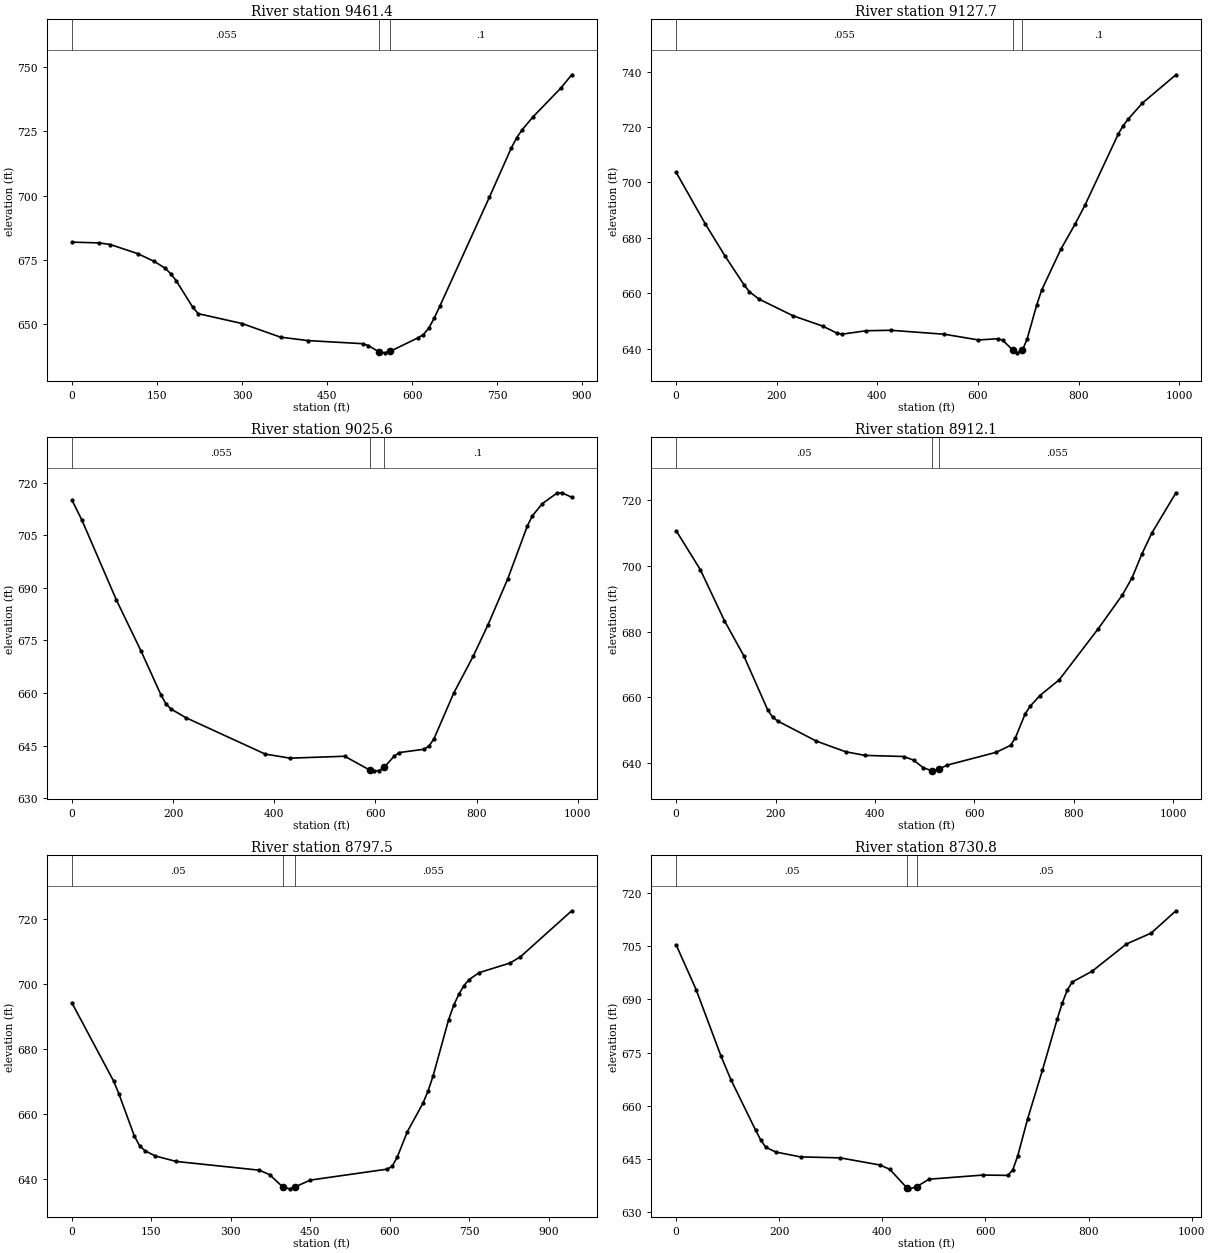
Type RM Length L Ch R = 1 ,9461.4  ,316.1,333.7,351.3
XS GIS Cut Line= 3
     1595633.443       460781.39     1595817.904       461042.24
      1596379.97      461053.091
#Sta/Elev= 30
       0  681.95    48.4  681.64    67.8  681.01   116.2  677.46   145.2  674.45
   164.6   671.8   174.3  669.66   183.9  666.96     213   656.7   222.7  654.17
   300.1  650.34     368  645.04   416.4  643.72   513.3  642.51     523  641.78
   541.8   639.3   552.1  638.96   561.8   639.6   610.3  644.77     620  646.07
   629.6   648.6   639.3  652.53     649  657.11   736.3  699.36     775  718.49
   784.7  722.53   794.4  725.64   813.8   730.7   862.3  741.74   881.6  746.93
#Mann= 3 , 0 , 0
       0    .055       0   541.8    .045       0   561.8      .1       0
Bank Sta=541.8,561.8
XS Rating Curve= 0 ,0
Exp/Cntr=0.3,0.1

Type RM Length L Ch R = 1 ,9127.7  ,111.6,102.1,92.9
XS GIS Cut Line= 4
     1595417.297      460952.397     1595846.116      461198.924
     1596007.575      461365.591     1596273.634      461387.292
#Sta/Elev= 30
       0  703.63    58.2  684.95      97  673.48   135.8  662.82   145.5  660.57
   164.9  657.88   232.8  651.85     291  648.18   320.1  645.57   329.8  645.25
   378.2  646.49   426.7  646.65   533.3  645.22     601  643.16   639.7   643.6
   649.3  643.04   668.7  639.61   678.3  638.51   688.5   639.5   697.7  643.48
     717  655.87   726.7  661.16   764.8   675.9   793.4  685.06   812.5  691.69
   879.2  717.55   888.8  720.52   898.3  722.76   926.9  728.64   993.6  738.85
#Mann= 3 , 0 , 0
       0    .055       0   668.7    .045       0   688.5      .1       0
Bank Sta=668.7,688.5
XS Rating Curve= 0 ,0
Exp/Cntr=0.3,0.1

Type RM Length L Ch R = 1 ,9025.6  ,105.2,113.5,121.2
XS GIS Cut Line= 4
     1595377.366      461018.369     1595610.005      461143.369
     1595939.866      461407.258     1596238.477      461448.924
#Sta/Elev= 30
       0  714.97    19.6  709.31      88  686.46   136.9  671.87   176.1  659.41
   185.8  656.89   195.6  655.45     225  652.98     382  642.59   431.1  641.42
   539.2  641.97   588.3  638.06   598.1  637.81   607.9   637.9   617.8   638.9
   637.4  642.06   647.2  643.02   696.2  643.97     706  644.91   715.7  646.95
   754.6  659.93   793.5  670.56   822.7  679.51   861.6  692.56   900.5  707.69
   910.2   710.5   929.7  713.96   958.8  716.98   968.6  717.08     988   715.8
#Mann= 3 , 0 , 0
       0    .055       0   588.3    .045       0   617.8      .1       0
Bank Sta=588.3,617.8
XS Rating Curve= 0 ,0
Exp/Cntr=0.3,0.1

Type RM Length L Ch R = 1 ,8912.1  ,116.8,114.6,111.9
XS GIS Cut Line= 4
     1595349.588      461068.716     1595512.783      461131.216
       1595898.2      461491.459     1596093.512      461723.664
#Sta/Elev= 30
       0  710.77    48.5  698.93    97.1  683.33   135.9  672.68   184.5  656.01
   194.3   653.9   204.1  652.75   282.2   646.6   340.8  643.37   379.9  642.25
   458.1  641.91   477.6  640.81   497.2  638.49   513.9  637.61   516.7  637.54
   528.9  638.11     546  639.31   643.7  643.18     673  645.31   682.8  647.68
   702.3  654.91   712.1   657.2   731.7  660.47   770.8   665.3   849.1  680.83
   898.1  691.23   917.6  696.48   937.2  703.67   956.8  709.96  1005.7  722.35
#Mann= 3 , 0 , 0
       0     .05       0   513.9    .045       0   528.9    .055       0
Bank Sta=513.9,528.9
XS Rating Curve= 0 ,0
Exp/Cntr=0.3,0.1

Type RM Length L Ch R = 1 ,8797.5  ,66.8,66.7,66.6
XS GIS Cut Line= 4
     1595340.474      461170.278     1595626.932      461393.803
     1595759.311      461489.289      1596069.64      461767.067
#Sta/Elev= 30
       0  694.13    78.6  670.12    88.4  666.29   117.8  653.21   127.7  650.28
   137.5  648.75   157.1  647.13   196.4  645.44   353.5  642.75     373  641.38
   398.7  637.45   411.4  637.02     421  637.62   449.8  639.71   594.4  643.06
   604.1  643.89   613.7  646.71   633.1  654.63   662.2  663.27   671.9  667.03
   681.5   671.7   710.6  688.88   720.3  693.35     730  696.78   739.7  699.44
   749.3   701.3   768.7  703.46   826.8   706.4   846.2  708.29   943.1  722.45
#Mann= 3 , 0 , 0
       0     .05       0   398.7    .045       0     421    .055       0
Bank Sta=398.7,421
XS Rating Curve= 0 ,0
Exp/Cntr=0.3,0.1

Type RM Length L Ch R = 1 ,8730.8  ,291.5,310.4,329.2
XS GIS Cut Line= 4
     1595238.477      461224.532     1595548.807      461419.844
     1595735.439      461552.223     1596019.727      461795.278
#Sta/Elev= 30
       0  705.38    38.6  692.81    86.8  674.09   106.1  667.41   154.4  653.07
     164   650.4   173.7  648.35     193     647   241.2  645.62   318.4  645.34
   395.3  643.33   414.4  642.11  447.15  636.95   452.5  636.61   466.3  637.19
   490.6  639.33   595.5   640.5   643.4   640.4     653  641.97   662.6  645.89
   681.8  656.34   710.6  670.09   739.4  684.56   748.9  688.96   758.5  692.58
   768.1  694.91   806.5  697.92   873.6  705.65   921.6  708.73   969.5  715.01
#Mann= 3 , 0 , 0
       0     .05       0  447.15    .045       0   466.3     .05       0
Bank Sta=447.15,466.3
XS Rating Curve= 0 ,0
Exp/Cntr=0.3,0.1