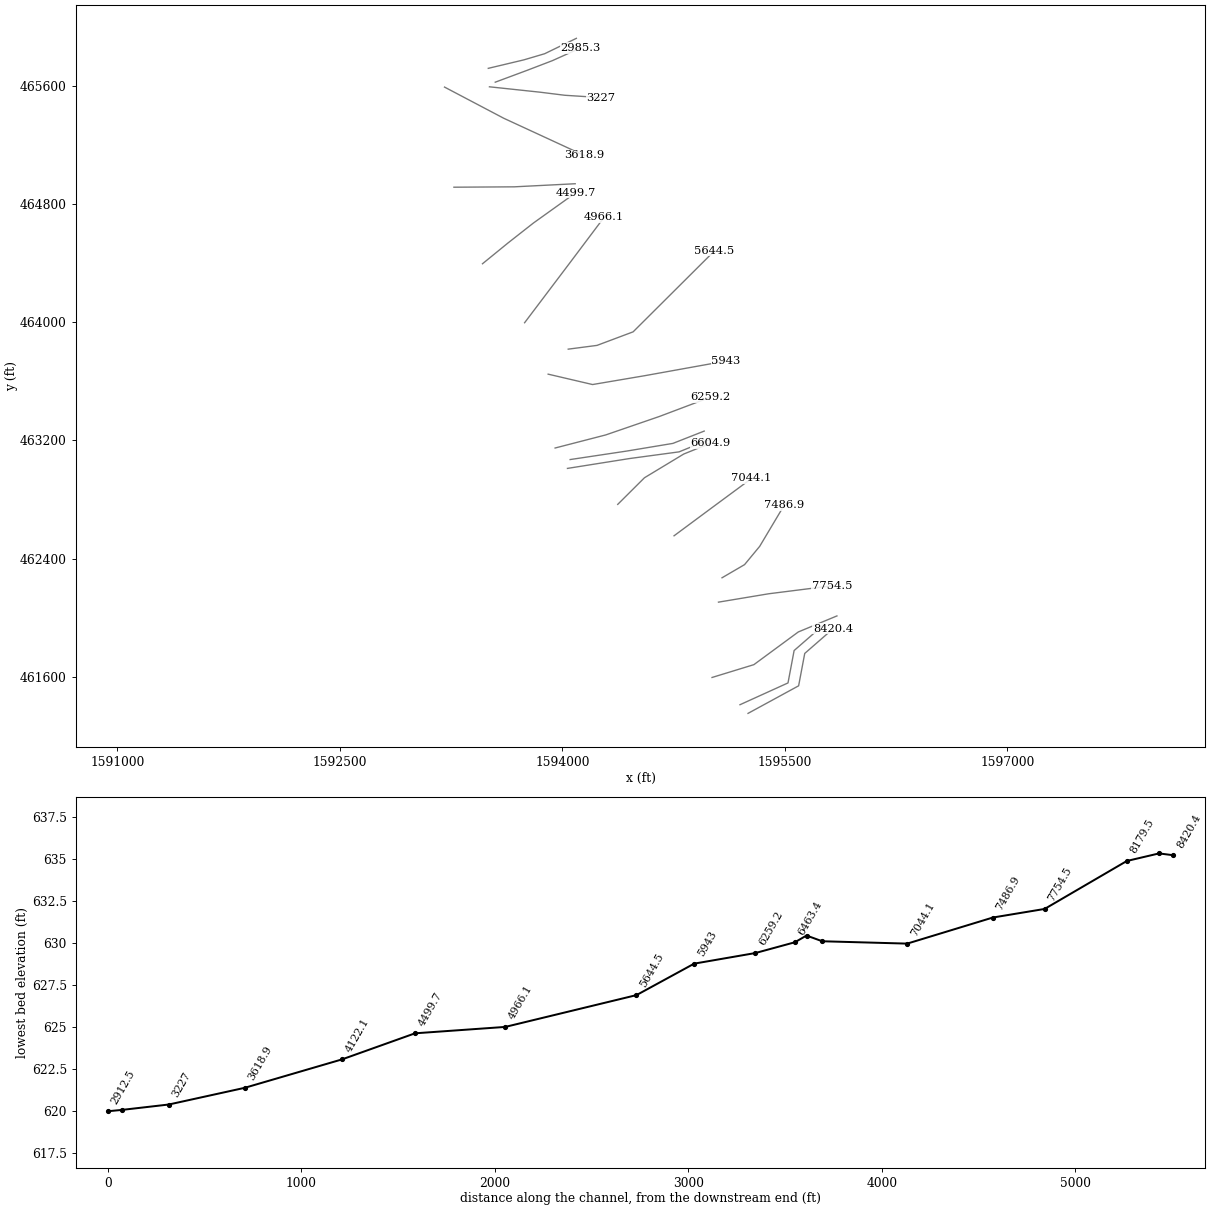
HEC-RAS study RaccoonCr.prj: RaccoonCr

--- RaccoonCr.g01 (geometry) --- (continued)

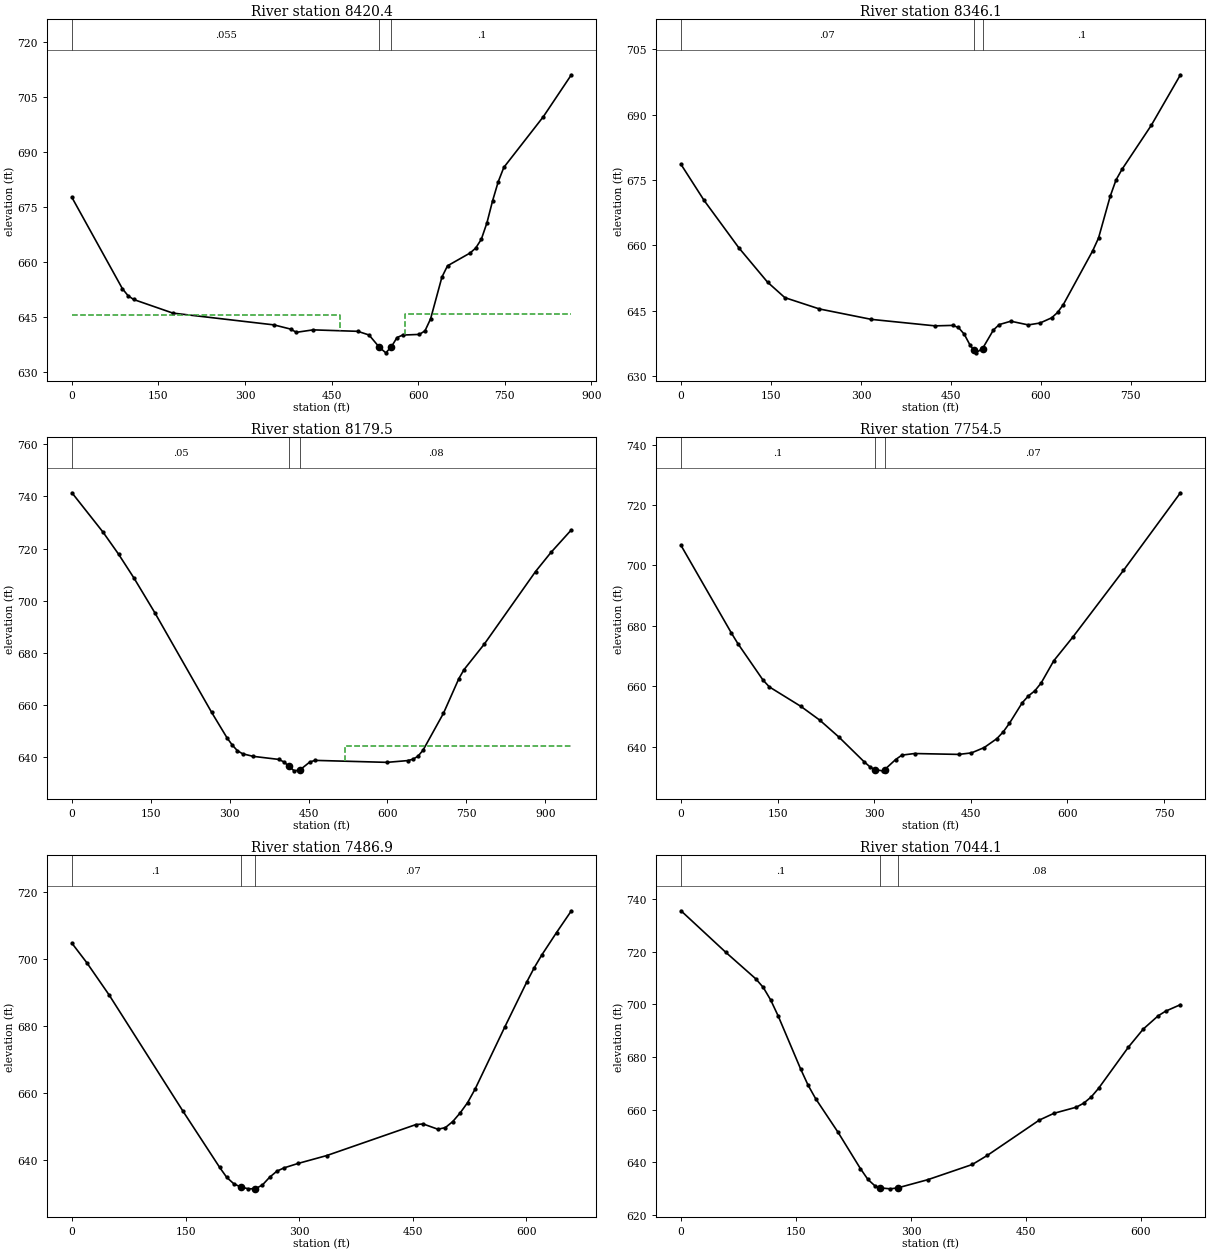
Type RM Length L Ch R = 1 ,8420.4  ,74.2,74.4,74.3
XS GIS Cut Line= 4
     1595251.498       461352.57     1595592.644      461539.202
     1595633.877      461758.386     1595824.849      461925.487
#Sta/Elev= 30
       0  677.61    87.5   652.7    97.2  650.81   106.9  649.77     175  646.05
     350  642.84   379.1  641.69   388.9  640.81     418  641.48   495.5  641.08
   514.9  640.08     533  636.69     544  635.21   553.7  636.89   563.4  639.38
   573.1  640.06   602.2  640.24   611.9  641.22   621.6  644.49   641.2  655.87
   650.9  658.96     690  662.45   699.7  663.79   709.5   666.2   719.2  670.67
     729  676.68   738.8   681.9   748.5  685.82   816.8  699.62   865.6   711.1
#Mann= 3 , 0 , 0
       0    .055       0     533    .045       0   553.7      .1       0
#XS Ineff= 2 , 0
          464.22  645.41  577.66          645.68
Permanent Ineff=
       F       F
Bank Sta=533,553.7
XS Rating Curve= 0 ,0
Exp/Cntr=0.3,0.1

Type RM Length L Ch R = 1 ,8346.1  ,183.3,166.6,149.1
XS GIS Cut Line= 4
     1595197.245      461411.164     1595521.029      461558.733
     1595562.262      461777.917     1595753.234      461945.018
#Sta/Elev= 30
       0  678.57    38.5   670.3    96.2  659.46   144.2  651.55   173.1  647.99
   230.8  645.39   317.4     643   423.7  641.51   452.8  641.62   462.5  641.14
   472.2  639.59   481.9  637.08   487.7  636.03   491.6  635.32   502.7  636.31
   520.7  640.54   530.4   641.8   549.8  642.58   578.9  641.73   598.4  642.16
   617.9  643.36   627.7  644.58   637.4  646.41   686.2  658.71     696  661.65
   715.5  671.25   725.2     675     735   677.4   783.8   687.5   832.6  699.14
#Mann= 3 , 0 , 0
       0     .07       0   487.7    .045       0   502.7      .1       0
Bank Sta=487.7,502.7
XS Rating Curve= 0 ,0
Exp/Cntr=0.3,0.1

Type RM Length L Ch R = 1 ,8179.5  ,435.3,425,414.3
XS GIS Cut Line= 4
     1595008.877      461595.626     1595290.995      461682.431
     1595590.474      461903.785      1595850.89      462012.292
#Sta/Elev= 30
       0   741.4      59  726.34    88.6  717.89   118.1  708.68   157.4  695.51
   265.6  657.28   295.2  647.41     305  644.71   314.8  642.55   324.6  641.41
   344.2  640.43   393.2  639.25     403   638.3   412.8  636.55   422.6  634.87
   433.4  635.21     452   638.2   461.8  638.88     599  638.12   638.2  638.79
     648  639.29   657.8  640.43   667.6  642.77   706.5  656.94   735.7  670.19
   745.4  673.61   784.3  683.48   881.6  711.24   910.8  718.53   949.7   727.2
#Mann= 3 , 0 , 0
       0     .05       0   412.8    .045       0   433.4     .08       0
#XS Ineff= 2 , 0
                          520.07          644.48
Permanent Ineff=
       F       F
Bank Sta=412.8,433.4
XS Rating Curve= 0 ,0
Exp/Cntr=0.3,0.1

Type RM Length L Ch R = 1 ,7754.5  ,251.2,267.6,283.7
XS GIS Cut Line= 3
     1595052.279      462105.608     1595390.529      462162.236
      1595819.69      462216.621
#Sta/Elev= 30
       0  706.64    78.4  677.58    88.2  674.17   127.4  662.05   137.2   659.8
   186.2  653.35   215.6  648.78     245  643.24   284.2  635.06     294  633.23
   301.2  632.38   313.6  632.02   316.2  632.41   333.2  635.74     343  637.22
   362.6  637.75   431.4  637.46   451.1  637.96   470.8  639.72   490.4  642.66
   500.3  644.88   510.1  647.79   529.8  654.52   539.6  656.84   549.4  658.49
   559.2  661.07   578.9  668.46   608.4  676.27   687.1  698.36   775.6  724.06
#Mann= 3 , 0 , 0
       0      .1       0   301.2    .045       0   316.2     .07       0
Bank Sta=301.2,316.2
XS Rating Curve= 0 ,0
Exp/Cntr=0.3,0.1

Type RM Length L Ch R = 1 ,7486.9  ,446.3,442.8,435.9
XS GIS Cut Line= 4
     1595076.151      462270.539     1595228.061      462359.515
     1595330.057      462483.212     1595494.988       462760.99
#Sta/Elev= 30
       0  704.79    19.6  698.99    48.9  689.42   146.7  654.64   194.9  637.95
   204.3  634.95   213.8     633   222.7  632.07   232.6  631.54   242.1  631.51
   251.5  632.67   260.9  634.95   270.4  636.75   279.8  637.75   298.6  639.09
   336.4  641.44   453.8  650.66   463.6  650.88   483.2  649.29     493  649.78
   502.8  651.59   512.6  654.18   522.4  657.24   532.2  661.24   571.3  679.72
   600.7  693.32   610.5  697.54   620.3  701.28   639.8  707.99   659.4  714.48
#Mann= 3 , 0 , 0
       0      .1       0   222.7    .045       0   242.1     .07       0
Bank Sta=222.7,242.1
XS Rating Curve= 0 ,0
Exp/Cntr=0.3,0.1

Type RM Length L Ch R = 1 ,7044.1  ,441.7,439.2,436.8
XS GIS Cut Line= 3
       1594752.8      462554.827     1595010.945      462746.993
     1595275.804      462943.282
#Sta/Elev= 30
       0  735.46    58.5  719.68    97.5  709.65   107.3  706.38     117   701.6
   126.8  695.52     156  675.47   165.8  669.27   175.5  664.23   204.8  651.44
     234  637.64   243.8  633.53   253.6  630.93  260.06  630.31   273.1  629.96
   282.8  630.33   321.8  633.42     380   639.2   399.4  642.61   467.3  656.03
   486.6  658.63   515.7  660.94   525.4  662.48   535.1  664.82   544.8  668.13
   583.6  683.72     603  690.58   622.4   695.6   632.1  697.36   651.5  699.84
#Mann= 3 , 0 , 0
       0      .1       0  260.06    .045       0   282.8     .08       0
Bank Sta=260.06,282.8
XS Rating Curve= 0 ,0
Exp/Cntr=0.3,0.1

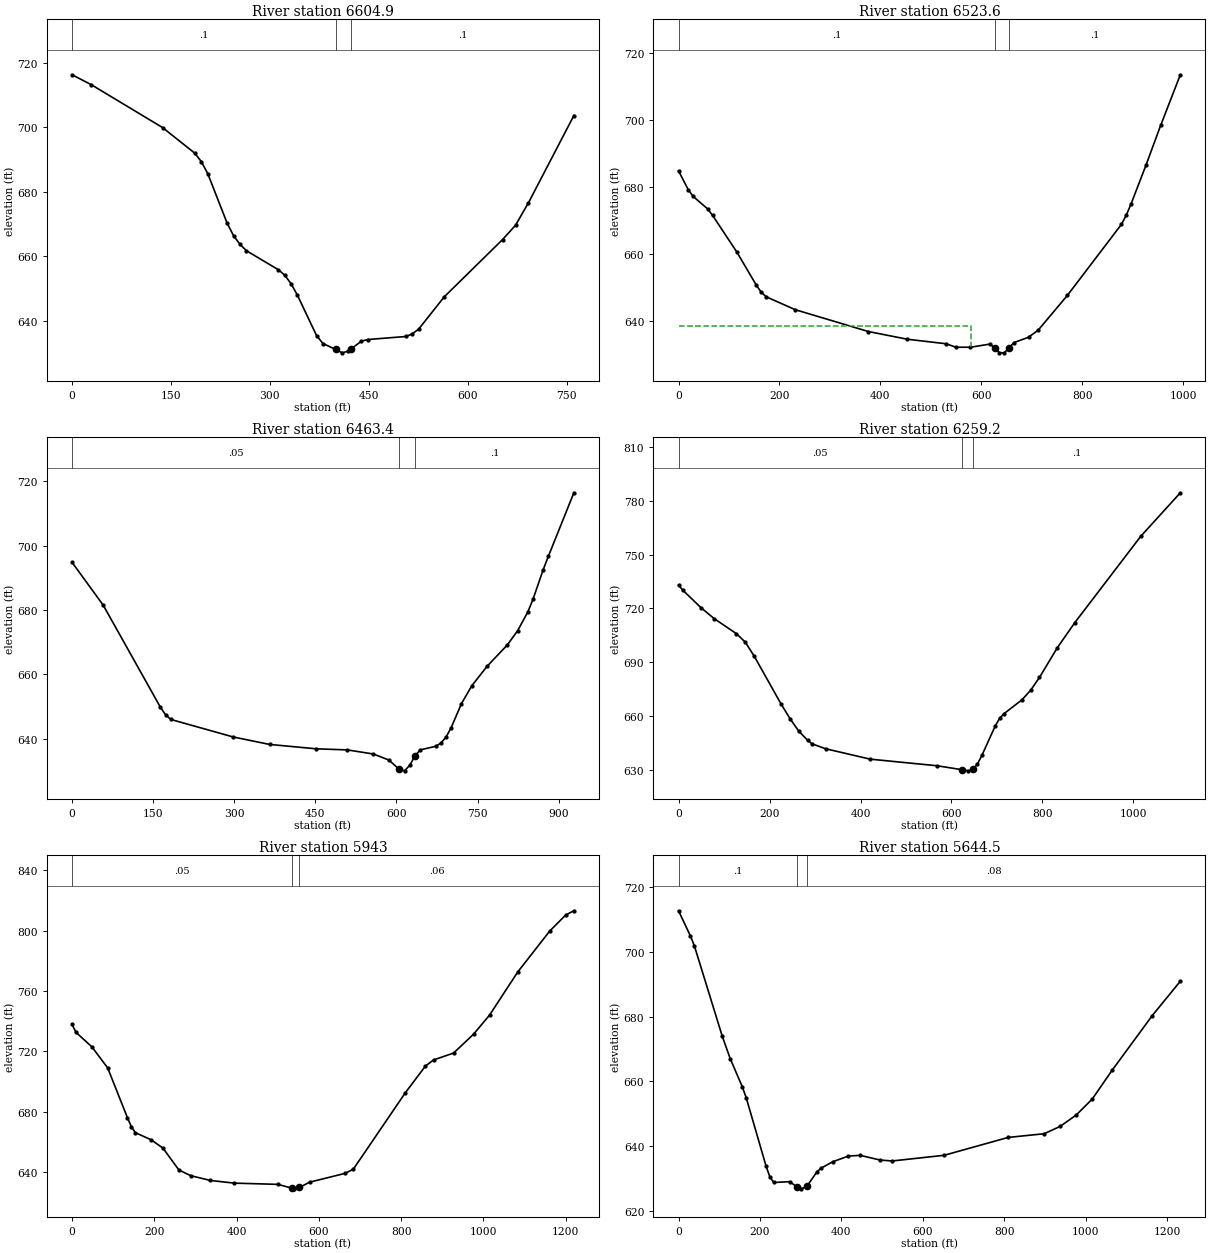
Type RM Length L Ch R = 1 ,6604.9  ,90.6,81.3,72
XS GIS Cut Line= 4
     1594373.026      462767.501     1594553.147      462947.622
     1594817.904      463108.212     1595000.196      463181.997
#Sta/Elev= 30
       0  716.31    29.4  713.21   137.2  699.95   186.2  691.99     196   689.4
   205.7   685.7   235.1  670.34   244.9  666.42   254.7  663.73   264.4  661.77
   312.8  655.87   322.5  654.19   332.1  651.54   341.8  647.96   370.8  635.44
   380.5  632.99   399.9  631.14   409.6   630.1   419.2  630.64  423.45  631.37
   438.6  633.69   448.3  634.22   506.3  635.17     516  635.98   525.7  637.47
   564.4  647.46   652.9  665.22   672.6  669.68   692.2  676.64     761  703.66
#Mann= 3 , 0 , 0
       0      .1       0   399.9    .045       0  423.45      .1       0
Bank Sta=399.9,423.45
XS Rating Curve= 0 ,0
Exp/Cntr=0.3,0.1

Type RM Length L Ch R = 1 ,6523.6  ,59.3,60.3,60.8
XS GIS Cut Line= 4
      1594034.05       463010.99     1594453.321      463077.831
     1594786.654      463122.969       1595002.8      463211.511
#Sta/Elev= 30
       0  684.76    19.3  679.11      29  677.12    57.9  673.37    67.5  671.45
   115.8  660.47   154.4  650.57     164  648.52   173.7  647.17   231.6   643.3
   376.3   636.8   453.4   634.5   530.3  633.15   549.5  632.12   578.3  632.11
   616.8  633.04   626.4  632.02     636  630.47   645.6  630.44   655.2  631.94
   664.8   633.5   693.7   635.1   712.9  637.23   770.7  647.59   877.7  668.77
   887.5  671.56   897.2  675.01   926.4  686.43   955.6  698.35   994.5  713.43
#Mann= 3 , 0 , 0
       0      .1       0   626.4    .045       0   655.2      .1       0
#XS Ineff= 2 , 0
          579.41  638.31
Permanent Ineff=
       F       F
Bank Sta=626.4,655.2
XS Rating Curve= 0 ,0
Exp/Cntr=0.3,0.1

Type RM Length L Ch R = 1 ,6463.4  ,200.8,204.2,206.3
XS GIS Cut Line= 4
     1594052.279      463070.886     1594432.488      463128.178
     1594744.988      463180.261     1594955.925      463263.594
#Sta/Elev= 30
       0  694.79    57.7  681.47   163.4  649.79     173  647.44   182.6     646
     298  640.56   365.3  638.24   451.7  636.88   509.3  636.54   557.3  635.27
   586.1  633.38   605.3  630.48   614.9  630.04   624.5  631.75   634.1   634.6
   643.7  636.54   672.5  637.66   682.1  638.66   691.7  640.52   701.3   643.5
   720.2  650.91   739.1  656.41   767.5  662.49   805.3  669.19   824.2   673.6
   843.1  679.44   852.5  683.32   871.4  692.51   880.9  696.66   928.1   716.4
#Mann= 3 , 0 , 0
       0     .05       0   605.3    .045       0   634.1      .1       0
Bank Sta=605.3,634.1
XS Rating Curve= 0 ,0
Exp/Cntr=0.3,0.1

Type RM Length L Ch R = 1 ,6259.2  ,319.8,316.2,314
XS GIS Cut Line= 4
     1593950.717      463149.011     1594291.863      463237.553
     1594653.842      463362.553     1594997.592      463492.761
#Sta/Elev= 30
       0  732.97     9.8  730.08      49  720.51    78.3  714.33   127.3  705.92
   146.8  701.17   166.4  693.36   225.2  666.78   244.8   658.6   264.3  651.54
   283.9  646.39   293.7  644.46   323.1  641.74   421.2  635.92   568.5  632.23
  622.74  630.05   637.2   629.4     647  630.19   656.8  633.06   666.7  637.96
   696.1  654.42   705.9  658.74   715.8  661.37   754.8  669.01   774.1  674.38
   793.4   681.5   832.1  697.89   870.8     712  1015.9   760.2    1103  784.53
#Mann= 3 , 0 , 0
       0     .05       0  622.74    .045       0     647      .1       0
Bank Sta=622.74,647
XS Rating Curve= 0 ,0
Exp/Cntr=0.3,0.1

Type RM Length L Ch R = 1 ,5943    ,297.1,298.4,300.3
XS GIS Cut Line= 4
     1593903.842      463649.011     1594203.321      463578.699
     1594554.884      463638.594     1595101.759      463737.553
#Sta/Elev= 30
       0  737.75     9.6  732.51    48.1  722.95    86.5     709   134.6  675.95
   144.2  669.94   153.8  666.05   192.3  661.27   221.1  655.76   259.6  641.29
   288.4  637.51   336.5  634.31   394.4  632.56   500.4  631.73   534.7   629.2
     539  628.77  552.69  629.68   577.5  633.18   664.2  639.06   683.8   641.8
   810.5  692.57   859.2  710.21   878.8  714.24   927.5   718.8   976.2  731.33
  1015.2  744.04  1083.5  772.57  1161.5  799.77  1200.5  810.42    1220  813.16
#Mann= 3 , 0 , 0
       0     .05       0   534.7    .045       0  552.69     .06       0
Bank Sta=534.7,552.69
XS Rating Curve= 0 ,0
Exp/Cntr=0.3,0.1

Type RM Length L Ch R = 1 ,5644.5  ,661.2,678.4,693.5
XS GIS Cut Line= 4
     1594039.259      463818.282     1594233.172      463843.729
     1594476.759      463935.469     1595026.238      464484.949
#Sta/Elev= 30
       0  712.63    29.3  704.85    39.1  701.74   107.6  673.89   127.1  667.01
   156.5   658.4   166.2  655.03   214.9  633.99   224.5  630.55   234.1  628.86
   272.7  629.11     292  627.44   301.6   626.9  315.32   627.7   340.2  632.15
   349.8  633.24   378.7  635.24   417.3     637   446.2  637.23   495.2  635.78
   524.7  635.49   652.6  637.24     810  642.75   898.5  643.89   937.8  646.16
   977.2  649.66  1016.5  654.57  1065.7  663.51  1164.1  680.33    1233  690.91
#Mann= 3 , 0 , 0
       0      .1       0     292    .045       0  315.32     .08       0
Bank Sta=292,315.32
XS Rating Curve= 0 ,0
Exp/Cntr=0.3,0.1

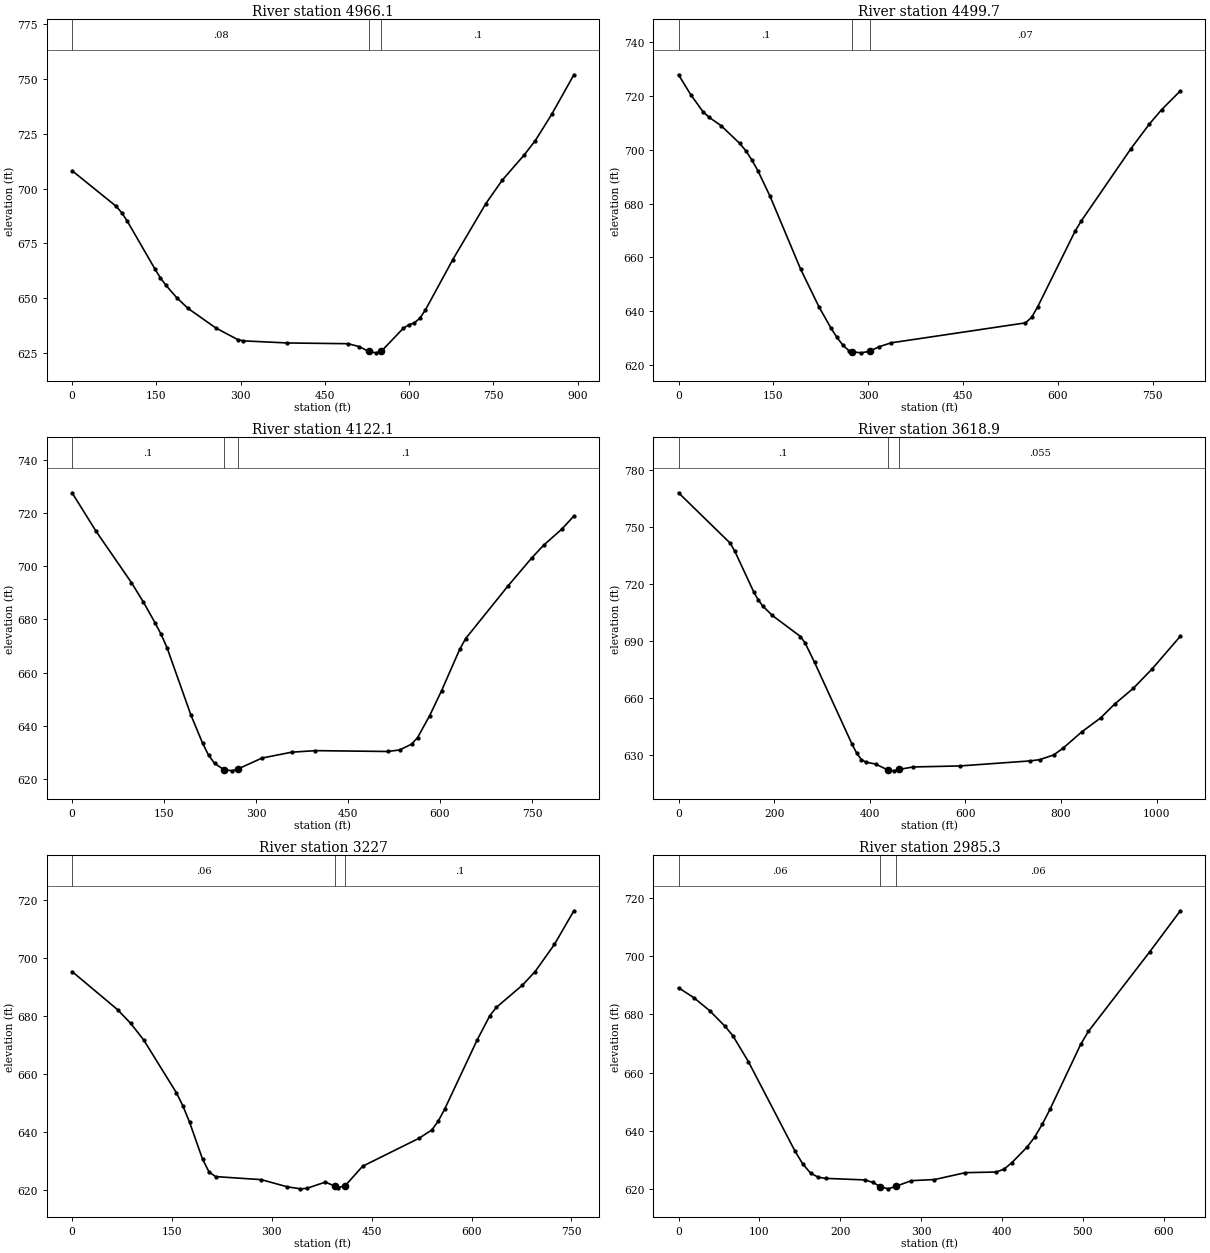
Type RM Length L Ch R = 1 ,4966.1  ,472.6,466.4,459.8
XS GIS Cut Line= 3
     1593745.058      463997.172     1594052.451      464405.631
     1594281.446      464711.511
#Sta/Elev= 30
       0   708.2    78.6  691.92    88.5  688.96    98.3  685.14   147.5  663.31
   157.3  659.25   167.1  655.86   186.8  650.07   206.4  645.32   255.6  636.41
   294.9  631.06   304.8  630.48   383.4  629.52   491.5  629.18   511.2  627.85
  528.21  625.63   540.6  625.01   550.4   625.7   589.6  636.21   599.4  637.79
   609.2  638.68     619  640.79   628.8  644.49   677.8   667.6   736.6  693.17
   765.9  703.89   805.1  715.44   824.7  721.96   854.1  734.03   893.3  751.99
#Mann= 3 , 0 , 0
       0     .08       0  528.21    .045       0   550.4      .1       0
Bank Sta=528.21,550.4
XS Rating Curve= 0 ,0
Exp/Cntr=0.3,0.1

Type RM Length L Ch R = 1 ,4499.7  ,392.4,377.6,361.3
XS GIS Cut Line= 4
     1593461.134      464396.407     1593633.009      464537.032
     1593804.884      464672.449     1594091.342      464878.178
#Sta/Elev= 30
       0  727.74    19.3  720.36    38.6  714.06    48.3  711.97    67.6  708.82
    96.6  702.32   106.2  699.65   115.9  696.16   125.5  692.15   144.8  682.66
   193.1  655.66   222.1   641.7   241.1  633.79   250.6  630.35   260.1  627.42
   269.6  625.42  274.62  625.03   288.7  624.63  302.06  625.19   317.2  626.89
   336.2  628.34   548.6  635.74   558.4  637.76   568.2  641.79     627  669.67
   636.8  673.49   715.2  700.25   744.6  709.47   764.2  714.85   793.6  721.76
#Mann= 3 , 0 , 0
       0      .1       0  274.62    .045       0  302.06     .07       0
Bank Sta=274.62,302.06
XS Rating Curve= 0 ,0
Exp/Cntr=0.3,0.1

Type RM Length L Ch R = 1 ,4122.1  ,511.6,503.2,497.1
XS GIS Cut Line= 3
     1593268.425      464914.636     1593674.974      464917.149
     1594086.134      464938.074
#Sta/Elev= 30
       0  727.54    38.7  713.23    96.8  693.79   116.2  686.52   135.5  678.61
   145.2  674.36   154.9   669.3   193.6  644.15     213  633.37   222.6  628.95
   232.3   625.9   247.2  623.57   261.4  623.08     271  623.84   309.8  627.89
   358.2  630.09   396.9  630.67   514.4  630.35     534  630.92   553.6   633.1
   563.4  635.59     583  643.78   602.6  653.24     632   668.7   641.8  672.79
   710.4  692.43   749.6  703.08   769.2  707.91   798.6   713.9   818.2   718.8
#Mann= 3 , 0 , 0
       0      .1       0   247.2    .045       0     271      .1       0
Bank Sta=247.2,271
XS Rating Curve= 0 ,0
Exp/Cntr=0.3,0.1

Type RM Length L Ch R = 1 ,3618.9  ,385.7,391.8,395
XS GIS Cut Line= 3
     1593205.156      465592.439     1593604.228      465381.511
     1594147.012       465129.78
#Sta/Elev= 30
       0  768.13   107.9  741.58   117.8  737.26     157  715.96   166.8  711.56
   176.6  708.26   196.2  703.39   255.1  692.28   264.9  688.79   284.6  678.61
   363.1  635.38   372.9  630.62   382.7  627.28   392.5  625.94   412.1  624.97
  437.95  621.84   451.4  621.39   461.2  622.12   490.6  623.44   588.7  623.97
   735.8  626.64   755.4  627.29   784.9  629.79   804.5  633.36   843.7  641.99
     883  649.32   912.4  656.64   951.6  665.01   990.8   675.2  1049.7  692.43
#Mann= 3 , 0 , 0
       0      .1       0  437.95    .045       0   461.2    .055       0
Bank Sta=437.95,461.2
XS Rating Curve= 0 ,0
Exp/Cntr=0.3,0.1

Type RM Length L Ch R = 1 ,3227    ,229.9,241.7,252.5
XS GIS Cut Line= 4
     1593508.009      465594.324     1593849.154      465557.865
     1594015.821      465537.032     1594258.009      465521.407
#Sta/Elev= 30
       0  695.34    68.6  682.14    88.2  677.42   107.8  671.67   156.8  653.49
   166.6  648.94   176.4  643.42     196  630.62   205.8  626.19   215.7  624.62
   284.3  623.57   323.5  621.08   343.1   620.4   352.4  620.56   380.4  622.72
   394.8  621.34   399.1  620.86   409.8  621.37   436.4  628.19   520.8   637.8
   540.2  640.68   549.9   643.7   559.6  647.86   608.1  671.58   627.5  680.12
   637.2  682.96   676.1  690.57   695.5  695.32   724.6  704.73   753.7  716.29
#Mann= 3 , 0 , 0
       0     .06       0   394.8    .045       0   409.8      .1       0
Bank Sta=394.8,409.8
XS Rating Curve= 0 ,0
Exp/Cntr=0.3,0.1

Type RM Length L Ch R = 1 ,2985.3  ,74.4,72.8,70.7
XS GIS Cut Line= 4
     1593547.071      465625.574     1593763.217      465706.303
     1593932.488      465771.407     1594122.592      465857.344
#Sta/Elev= 30
       0  689.16    19.2   685.7    38.4  681.31    57.7  675.88    67.3  672.64
    86.5  663.74   144.2  632.97   153.8  628.57   163.4  625.46     173  624.04
   182.7  623.67   230.7  623.14   240.3  622.29   249.8  620.81   259.4  620.08
   268.9  620.96     288  622.89   316.6  623.27   354.8  625.64     393  625.86
   402.5  626.83   412.1  629.01     431  634.38   440.5  637.84     450   642.3
   459.5  647.42   497.4  669.69   506.9  674.15   582.8  701.49   620.7  715.61
#Mann= 3 , 0 , 0
       0     .06       0   249.8    .045       0   268.9     .06       0
Bank Sta=249.8,268.9
XS Rating Curve= 0 ,0
Exp/Cntr=0.3,0.1

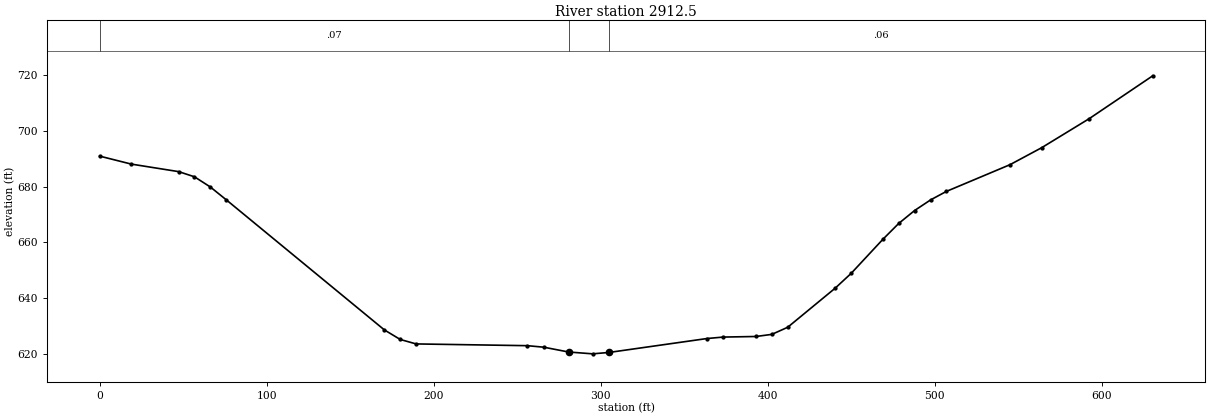
Type RM Length L Ch R = 1 ,2912.5  ,223.7,222.1,220.1
XS GIS Cut Line= 4
     1593500.196      465719.324     1593739.779      465776.615
     1593880.404      465818.282     1594093.946      465922.449
#Sta/Elev= 30
       0     691      19  688.13    47.4  685.42    56.8  683.57    66.3  679.91
    75.8  675.32   170.5  628.59     180  625.16   189.5  623.56   256.1  622.93
   265.9  622.39   280.8  620.66   295.2     620     305   620.5   363.7   625.5
   373.4  626.02     393  626.23   402.5  626.99     412  629.54   440.5  643.61
     450  648.89     469  661.13   478.5  666.83     488  671.47   497.6  675.29
     507  678.32   545.1  687.92   564.1  694.03   592.6  704.47   630.6  719.85
#Mann= 3 , 0 , 0
       0     .07       0   280.8    .045       0     305     .06       0
Bank Sta=280.8,305
XS Rating Curve= 0 ,0
Exp/Cntr=0.3,0.1