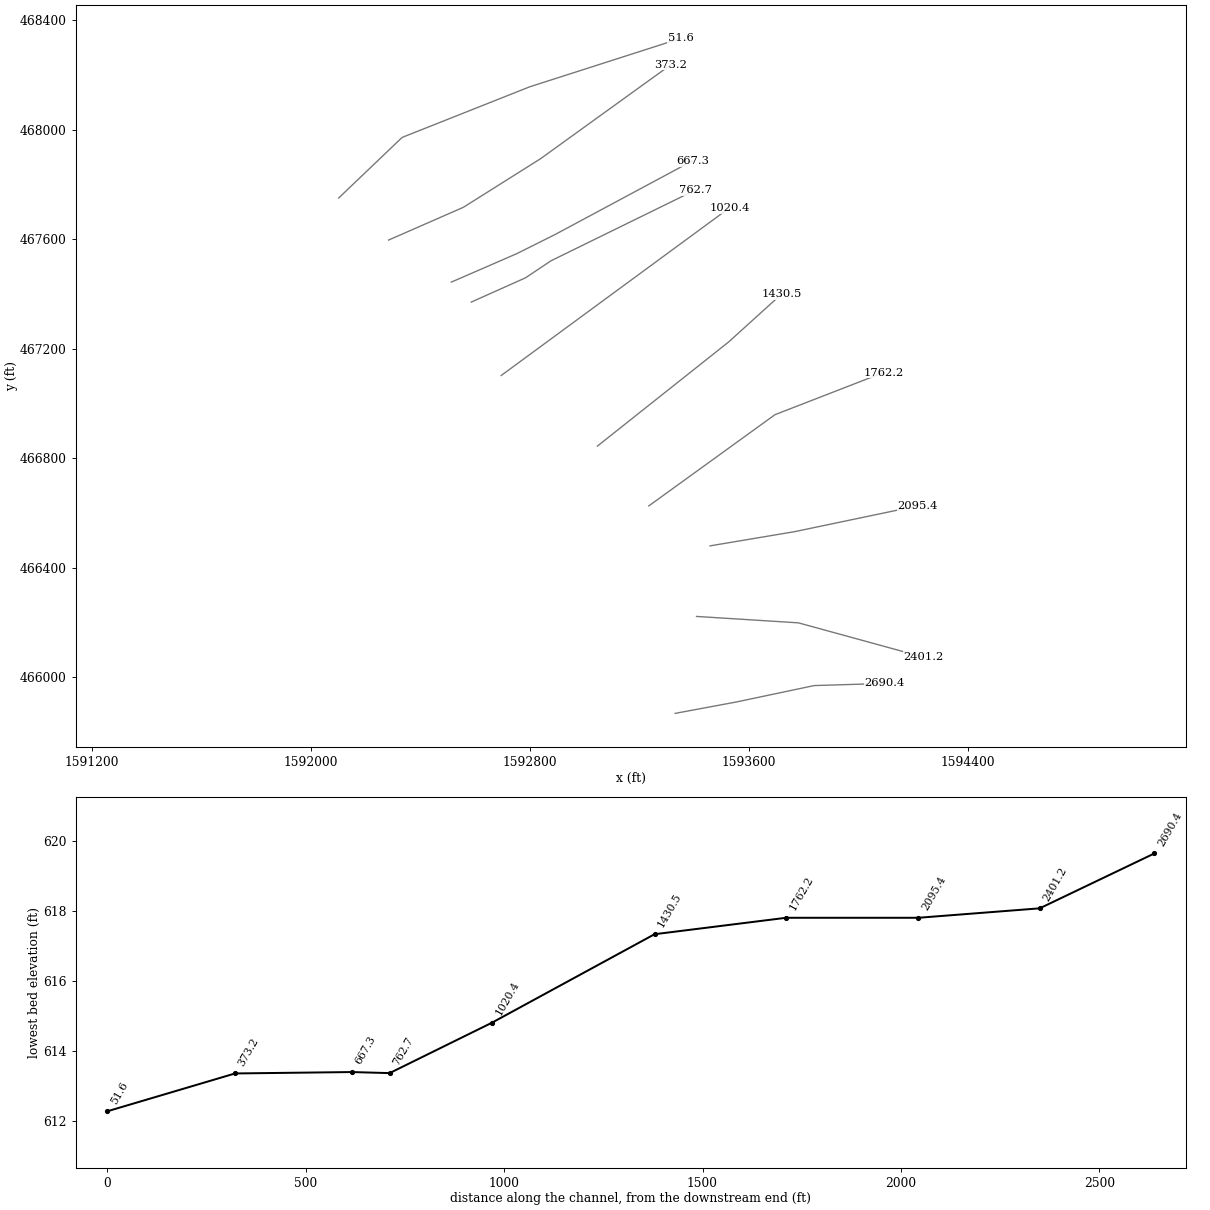
HEC-RAS study RaccoonCr.prj: RaccoonCr

--- RaccoonCr.g01 (geometry) --- (continued)

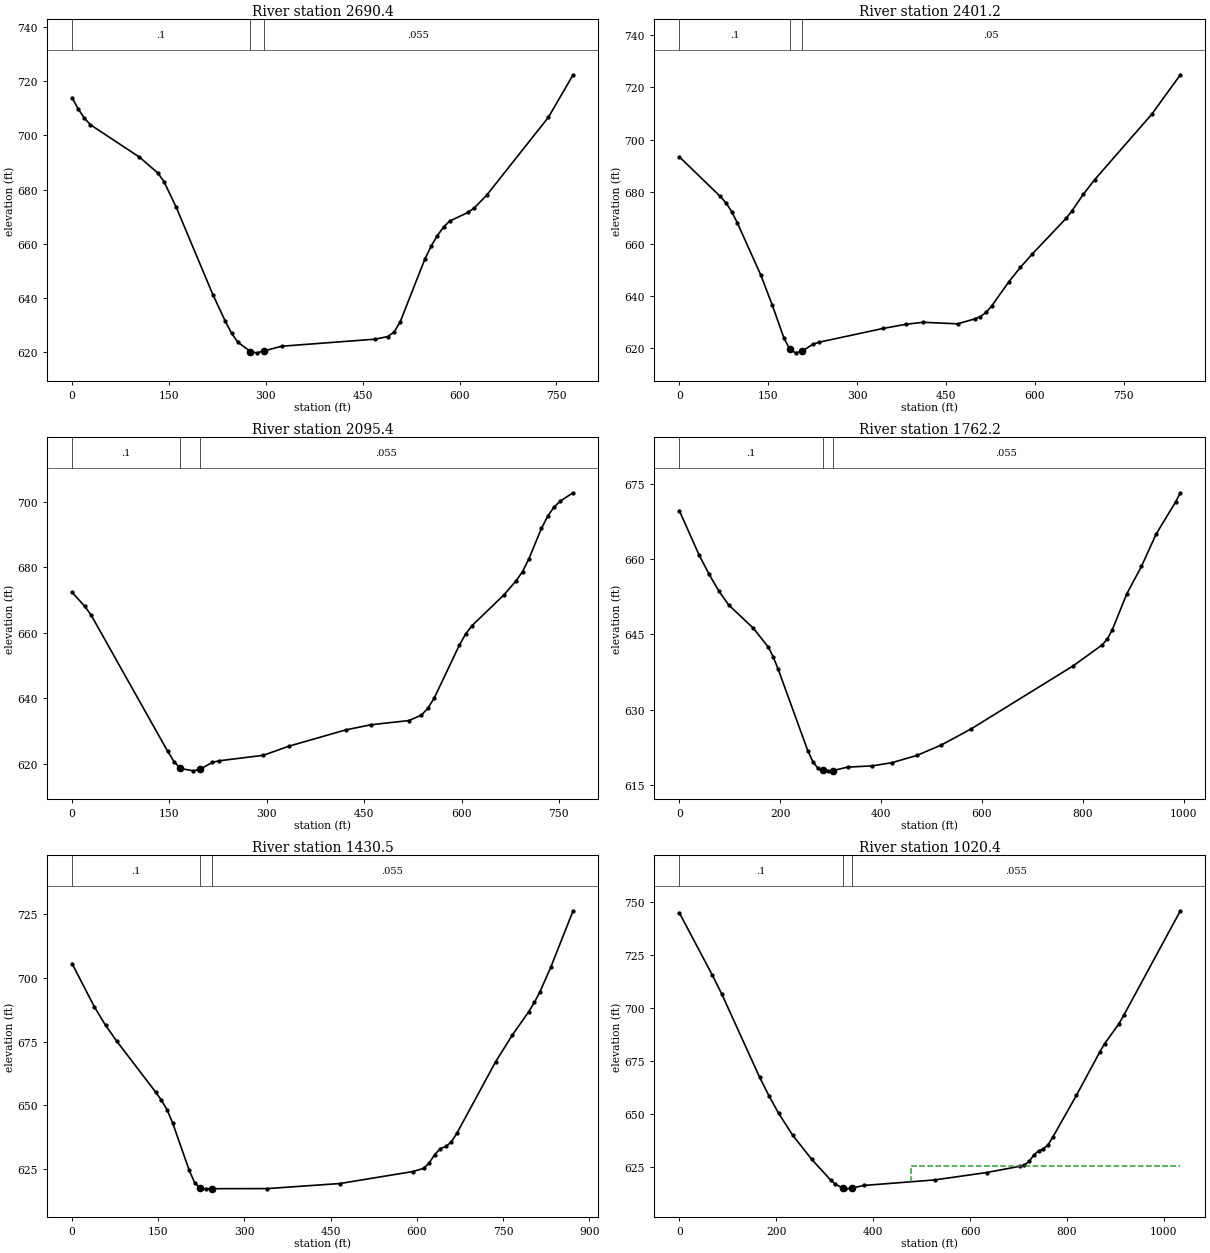
Type RM Length L Ch R = 1 ,2690.4  ,295.3,289.2,283.1
XS GIS Cut Line= 4
     1593330.925      465867.761     1593554.884      465909.428
     1593838.738      465969.324      1594096.55      465977.136
#Sta/Elev= 30
       0  713.99     9.5  709.81      19  706.43    28.5  703.95   104.4  691.97
   132.9  686.11   142.4  682.92   161.4  673.42   218.3  641.03   237.5  631.24
   247.1  626.85   256.8  623.56   276.2  620.14   285.8  619.65     297  620.33
   324.5  622.09   469.6  624.71   488.9  625.68   498.6  627.32   508.2  631.17
   546.6  654.48   556.1  659.11   565.7     663   575.2  666.13   584.8  668.36
   613.4  671.57     623  673.26   642.1  677.94   737.6  706.72   775.8  722.42
#Mann= 3 , 0 , 0
       0      .1       0   276.2    .045       0     297    .055       0
Bank Sta=276.2,297
XS Rating Curve= 0 ,0
Exp/Cntr=0.3,0.1

Type RM Length L Ch R = 1 ,2401.2  ,300.6,305.8,310.9
XS GIS Cut Line= 3
      1593409.05      466221.928     1593781.446       466198.49
     1594237.175       466073.49
#Sta/Elev= 30
       0  693.38    68.7  678.26    78.6  675.75    88.4  672.35    98.2  667.88
   137.5  647.99   157.1  636.31   176.8  623.64   186.6  619.43   196.4  618.08
   206.9  618.66   225.8  621.43   235.7  622.15   343.7  627.44   382.8  629.05
   411.7  629.82   469.6  629.22   498.5   631.1   508.2  632.03   517.8  633.61
   527.4  636.14   556.4  645.42   575.7  650.92     595  655.86   652.8  669.72
   662.5  672.53   681.7  678.91     701  684.57   797.5  709.75   845.7  724.88
#Mann= 3 , 0 , 0
       0      .1       0   186.6    .045       0   206.9     .05       0
Bank Sta=186.6,206.9
XS Rating Curve= 0 ,0
Exp/Cntr=0.3,0.1

Type RM Length L Ch R = 1 ,2095.4  ,322.5,333.3,343.4
XS GIS Cut Line= 3
     1593458.529       466479.74     1593768.425      466531.824
     1594216.342      466625.574
#Sta/Elev= 30
       0  672.33    19.6  668.07    29.5  665.34   147.3  623.78   157.1  620.65
   166.9  618.54   186.6  617.81   196.4  618.22     216  620.37   225.9  620.86
   294.6  622.55   333.7  625.32   421.4   630.3   460.3  631.88   518.7  633.16
   538.2  634.81   547.9  636.87   557.7  639.92   596.6  656.17   606.3   659.6
   616.1  662.14   664.8  671.44   684.2  675.86     694  678.66   703.7  682.52
   723.2  691.87   732.9  695.61   742.6  698.37   752.4  700.23   771.9  702.73
#Mann= 3 , 0 , 0
       0      .1       0   166.9    .045       0   196.4    .055       0
Bank Sta=166.9,196.4
XS Rating Curve= 0 ,0
Exp/Cntr=0.3,0.1

Type RM Length L Ch R = 1 ,1762.2  ,329.9,331.7,332.2
XS GIS Cut Line= 3
     1593234.571      466625.574     1593695.509      466958.907
     1594091.342      467112.553
#Sta/Elev= 30
       0  669.66    39.2  660.83    58.8  657.02    78.5  653.62    98.1  650.84
   147.1   646.2   176.5  642.45   186.3   640.5   196.2  638.01     255  621.75
   264.8  619.65   274.6  618.34   284.4  617.88   294.2  617.81     304  617.84
   333.5  618.55   382.5   618.8   421.7  619.44   470.8  620.87   519.8  622.97
   578.5  626.16   781.1  638.74     839  642.95   848.7  644.12   858.3  645.88
   887.3   653.1   916.2  658.53   945.2  664.95   983.8  671.36   993.4  673.21
#Mann= 3 , 0 , 0
       0      .1       0   284.4    .045       0     304    .055       0
Bank Sta=284.4,304
XS Rating Curve= 0 ,0
Exp/Cntr=0.3,0.1

Type RM Length L Ch R = 1 ,1430.5  ,411,410,409.4
XS GIS Cut Line= 3
     1593047.071      466844.324     1593526.238      467224.532
     1593718.946      467399.011
#Sta/Elev= 30
       0  705.51    38.8   688.6    58.3  681.34    77.7  675.16   145.6  655.15
   155.4  652.05   165.1  648.38   174.8  643.24   203.9  624.57   213.6   619.6
   223.3  617.68     233  617.34   242.7   617.4   339.8  617.44     466  619.42
   592.3  624.09   611.7  625.34   621.3  627.52   630.9  630.75   640.6  633.07
   650.2  633.91   659.8  635.73   669.4  639.08   736.8  667.05   765.7  677.45
   794.6  686.71   804.2  690.28   813.9  694.41   833.1  704.25   871.6  726.16
#Mann= 3 , 0 , 0
       0      .1       0   223.3    .045       0   242.7    .055       0
Bank Sta=223.3,242.7
XS Rating Curve= 0 ,0
Exp/Cntr=0.3,0.1

Type RM Length L Ch R = 1 ,1020.4  ,257.3,257.8,258.9
XS GIS Cut Line= 2
     1592695.509      467102.136     1593528.842      467714.115
#Sta/Elev= 30
       0   745.1    68.3   715.6    87.8  706.67   165.8  667.43   185.3  658.58
   204.8  650.52   234.1  640.07   273.1  628.76   312.1  619.02   321.9  617.04
   337.1  615.17   341.4  614.81  355.85  615.16   380.4   616.4   526.7  619.01
     634   622.5   702.3  625.43     712  626.04   721.8  627.78   731.5  630.78
   741.3  632.74     751  633.62   760.8  635.57   770.6  639.17   819.3  658.88
   868.1   679.6   877.8  683.38   907.1  692.69   916.9  696.62  1033.9  746.03
#Mann= 3 , 0 , 0
       0      .1       0   337.1    .045       0  355.85    .055       0
#XS Ineff= 2 , 0
                          477.49          625.36
Permanent Ineff=
       F       F
Bank Sta=337.1,355.85
XS Rating Curve= 0 ,0
Exp/Cntr=0.3,0.1

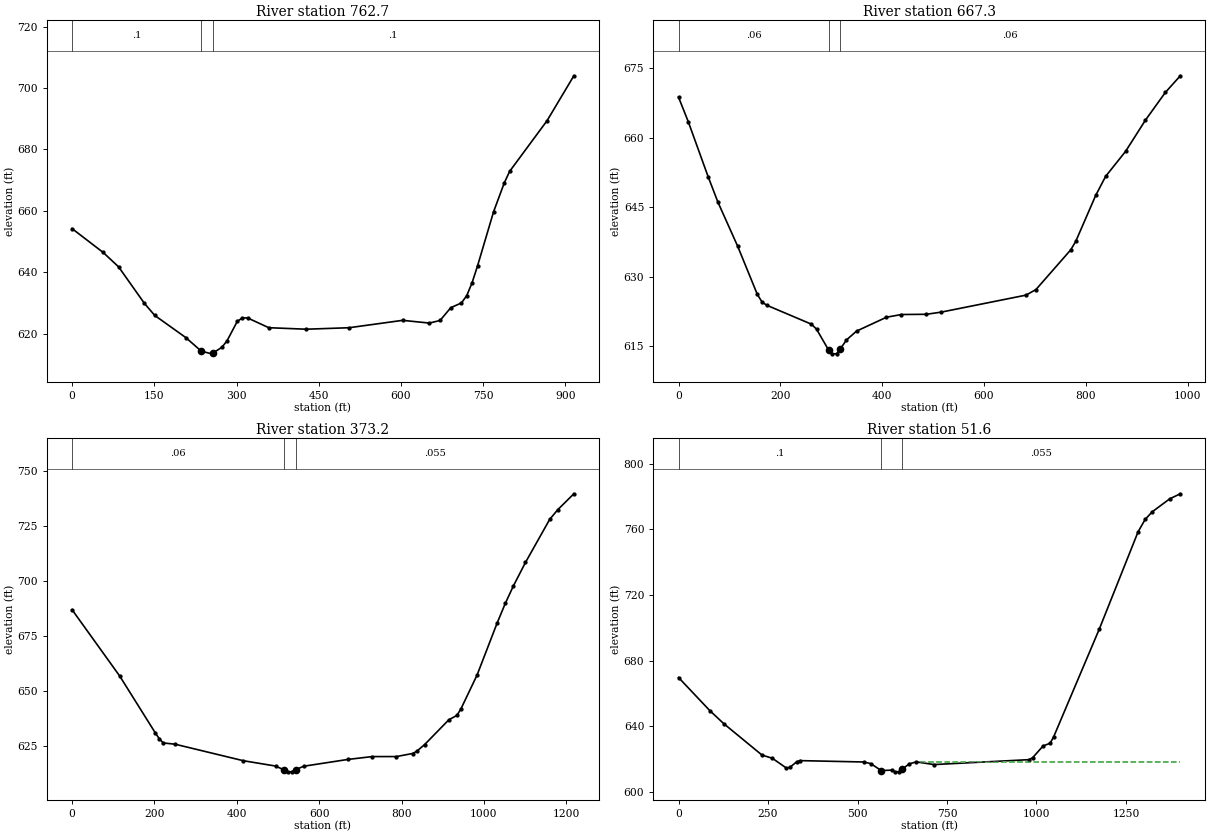
Type RM Length L Ch R = 1 ,762.7   ,99.6,95.4,90.1
XS GIS Cut Line= 4
     1592586.134      467370.365      1592784.05      467458.907
       1592877.8      467521.407     1593403.842      467779.219
#Sta/Elev= 30
       0  654.19    56.6  646.44    84.8  641.74     132  629.81   150.8  625.89
   207.4  618.68   235.6  614.26   254.4  613.37   256.4  613.56   273.2   615.5
   282.6  617.59   301.3  623.94   310.7  625.09   320.1  625.08   358.8  621.89
   427.1   621.4   505.2  621.88   602.9  624.29   651.7   623.4   671.2  624.24
   690.8  628.42   710.3  629.97     720  632.38   729.8  636.62   739.6  642.04
   768.9  659.71   788.4  669.11   798.2  672.87   866.5   689.4   915.3  704.02
#Mann= 3 , 0 , 0
       0      .1       0   235.6    .045       0   256.4      .1       0
Bank Sta=235.6,256.4
XS Rating Curve= 0 ,0
Exp/Cntr=0.3,0.1

Type RM Length L Ch R = 1 ,667.3   ,288.7,294.1,296.7
XS GIS Cut Line= 4
     1592513.217      467443.282       1592752.8      467547.449
     1592893.425      467617.761     1593393.425       467885.99
#Sta/Elev= 30
       0  668.76    19.4  663.38    58.1  651.62    77.4  646.11   116.1  636.63
   154.8  626.22   164.5  624.51   174.2  623.84   261.2  619.79   271.1  618.73
  294.94   614.2   300.6   613.4   310.4  613.41  317.11  614.34     330   616.4
   349.7   618.3   408.6   621.3     438  621.88     487  621.93   516.3   622.4
   682.6  626.06   702.2  627.26   770.6  635.83   780.4  637.65   819.6  647.56
   839.1  651.67   878.3  657.06   917.4  663.81   956.5  669.78   985.9  673.37
#Mann= 3 , 0 , 0
       0     .06       0  294.94    .045       0  317.11     .06       0
Bank Sta=294.94,317.11
XS Rating Curve= 0 ,0
Exp/Cntr=0.3,0.1

Type RM Length L Ch R = 1 ,373.2   ,326,321.7,315.7
XS GIS Cut Line= 4
      1592284.05      467596.928     1592557.488      467716.719
     1592838.738      467893.803       1593315.3      468237.553
#Sta/Elev= 30
       0  687.11   115.6  656.96   202.2  631.06   211.9  628.38   221.5  626.51
   250.4  625.92   415.8  618.42     494     616   513.6  614.35   523.4  613.36
   533.1  613.39   542.9  614.36   562.5  615.91   670.1  619.01   728.8   620.3
   787.6  620.31   826.8   621.7   836.5  622.66   856.1  625.76   914.9  637.04
   934.5  639.03   944.3     642   983.4  657.36  1032.4  681.15    1052  689.97
  1071.6  697.91    1101  708.61  1159.7  728.17  1179.3  732.59  1218.5  739.85
#Mann= 3 , 0 , 0
       0     .06       0   513.6    .045       0   542.9    .055       0
Bank Sta=513.6,542.9
XS Rating Curve= 0 ,0
Exp/Cntr=0.3,0.1

Type RM Length L Ch R = 1 ,51.6    ,60.1,51.6,42.8
XS GIS Cut Line= 4
     1592101.759      467750.574     1592333.529      467971.928
     1592799.675      468156.824     1593351.759      468333.907
#Sta/Elev= 30
       0  669.74    87.4  649.58   126.2  641.66   233.1   622.5   262.2  620.54
   301.1   614.6   310.8  614.95   330.3  618.45   340.2  619.11   517.2  618.28
   536.8  617.31   566.3  613.07   595.8  613.33   605.6  612.28   615.5  612.39
   625.3     614     645   617.2   664.6  618.33   713.8  616.71   979.2   619.7
     989  620.84  1018.5  628.06  1038.2   629.7    1048  633.64  1175.7  699.39
  1283.8   758.5  1303.5  766.04  1323.1  770.65  1372.3  778.61  1401.8  781.67
#Mann= 3 , 0 , 0
       0      .1       0   566.3    .045       0   625.3    .055       0
#XS Ineff= 2 , 0
          515.67  618.22  674.68          618.27
Permanent Ineff=
       F       F
Bank Sta=566.3,625.3
XS Rating Curve= 0 ,0
Exp/Cntr=0.3,0.1

Chan Stop Cuts=-1
Use User Specified Reach Order=0
Composite Channel Slope=5